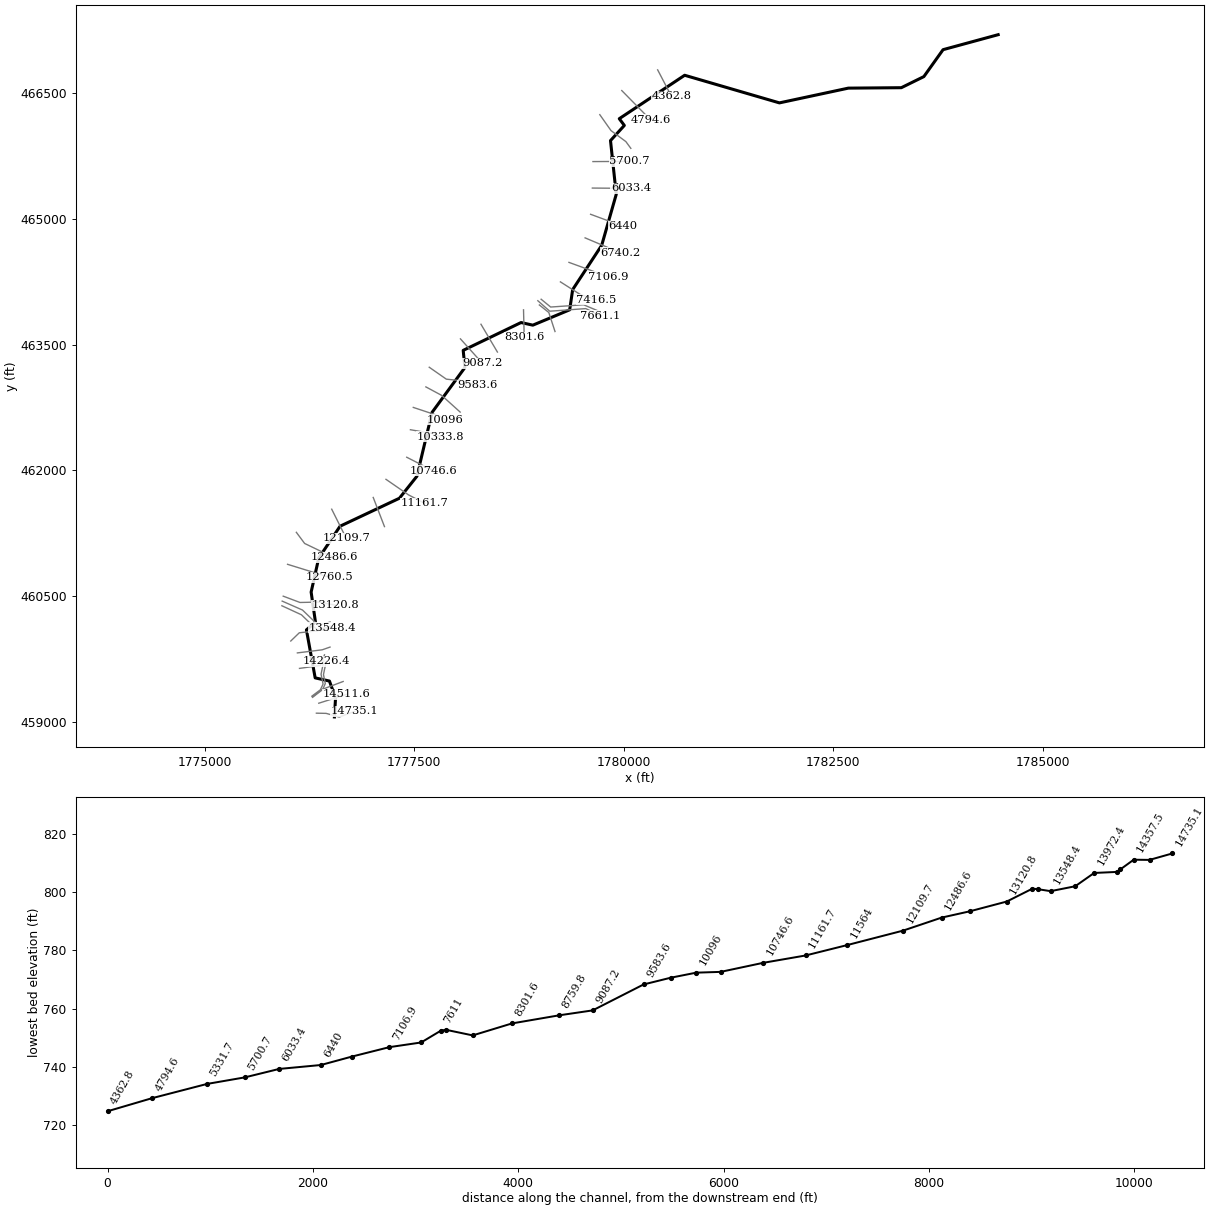
--- DAVISCK.prj (project) ---

Proj Title=DAVISCK
Current Plan=p01
Default Exp/Contr=0,0
English Units
Geom File=g01
Flow File=f01
Plan File=p01
BEGIN DESCRIPTION:
END DESCRIPTION:
DSS Export Rating Curves= 0
DSS Export Rating Curve Sorted= 0
DSS Export Volume Flow Curves= 0
DXF OffsetX= 0
DXF OffsetY= 0
DXF ScaleX= 0
DXF ScaleY= 0

--- DAVISCK.p01 (plan) ---

Plan Title=Floodplain
Program Version=4.00
Geom File=g01
Flow File=f01
K Sum by GR=0
Std Step Tol=0.01
Critical Tol=0.01
Num of Std Step Trials=20
Max Error Tol=0.3
Flow Tol Ratio=0.001
Split Flow NTrial=30
Split Flow Tol=0.02
Split Flow Ratio=0.02
Log Output Level=0
Friction Slope Method=1
Unsteady Friction Slope Method=2
Unsteady Bridges Friction Slope Method=1
Global Log Level=0
CheckData=False
Run HTab=0
Run UNet=0
Run PostProcess=0
UNET Theta=0
UNET Theta Warmup=0
UNET ZTol=0
UNET ZSATol=0
UNET MxIter=0
UNET MaxInSteps=0
UNET DtIC=0
UNET DtMin=0
UNET MaxCRTS=0
UNET WFStab=0
UNET SFStab=0
UNET WFX=0
UNET SFX=0
UNET DSS MLevel=0
UNET DZMax Abort=0
UNET Convert EG Bridges=0
UNET Use Existing IB Tables=0
UNET Froude Limit=0
UNET Froude Power=0
Write IC File=0
Echo Input=False
Echo Output=False
Write Detailed=0

--- DAVISCK.f01 (steady flow) ---

Flow Title=NFF Regression Equation
Program Version=4.10
Number of Profiles= 1
Profile Names=P100yr
River Rch & RM=DAVISCK,Main            ,14735.1
1119.775
River Rch & RM=DAVISCK,Main            ,13422.6
 1147.16
River Rch & RM=DAVISCK,Main            ,13120.8
1385.745
River Rch & RM=DAVISCK,Main            ,11564
1480.077
River Rch & RM=DAVISCK,Main            ,7106.9
1643.852
River Rch & RM=DAVISCK,Main            ,6740.2
1873.984
River Rch & RM=DAVISCK,Main            ,628.3
2084.619
Boundary for River Rch & Prof#=DAVISCK,Main            , 1
Up Type= 0
Dn Type= 1
Dn Known WS=708.2
DSS Import GetInterval= 0
DSS Import GetPeak= 0
DSS Import FillOption= 0

--- DAVISCK.g01 (geometry) ---

Geom Title=USGS 10m DEM
Program Version=4.10

River Reach=DAVISCK         ,Main
Reach XY= 30
     1776547.226       459058.58     1776560.594      459284.969
     1776487.937      459486.532     1776317.608      459524.581
     1776213.357      460097.194     1776321.003      460189.587
     1776269.484      460548.303     1776359.909      460953.125
     1776614.564      461333.755     1777322.268      461667.262
     1777531.382      461930.023     1777711.907      462691.582
     1778103.834      463226.738     1778083.487      463431.498
     1778773.409      463763.512     1778914.295      463732.262
     1779353.912      463915.507     1779389.407      464156.552
     1779735.709      464684.681     1779909.321      465293.405
     1779840.769      465933.971      1780005.86      466114.756
     1779945.443      466195.225      1780725.33      466713.374
     1781855.935        466383.9     1782678.168      466559.903
     1783310.113      466565.112     1783579.025      466697.485
     1783807.975      467018.665     1784465.477      467197.548

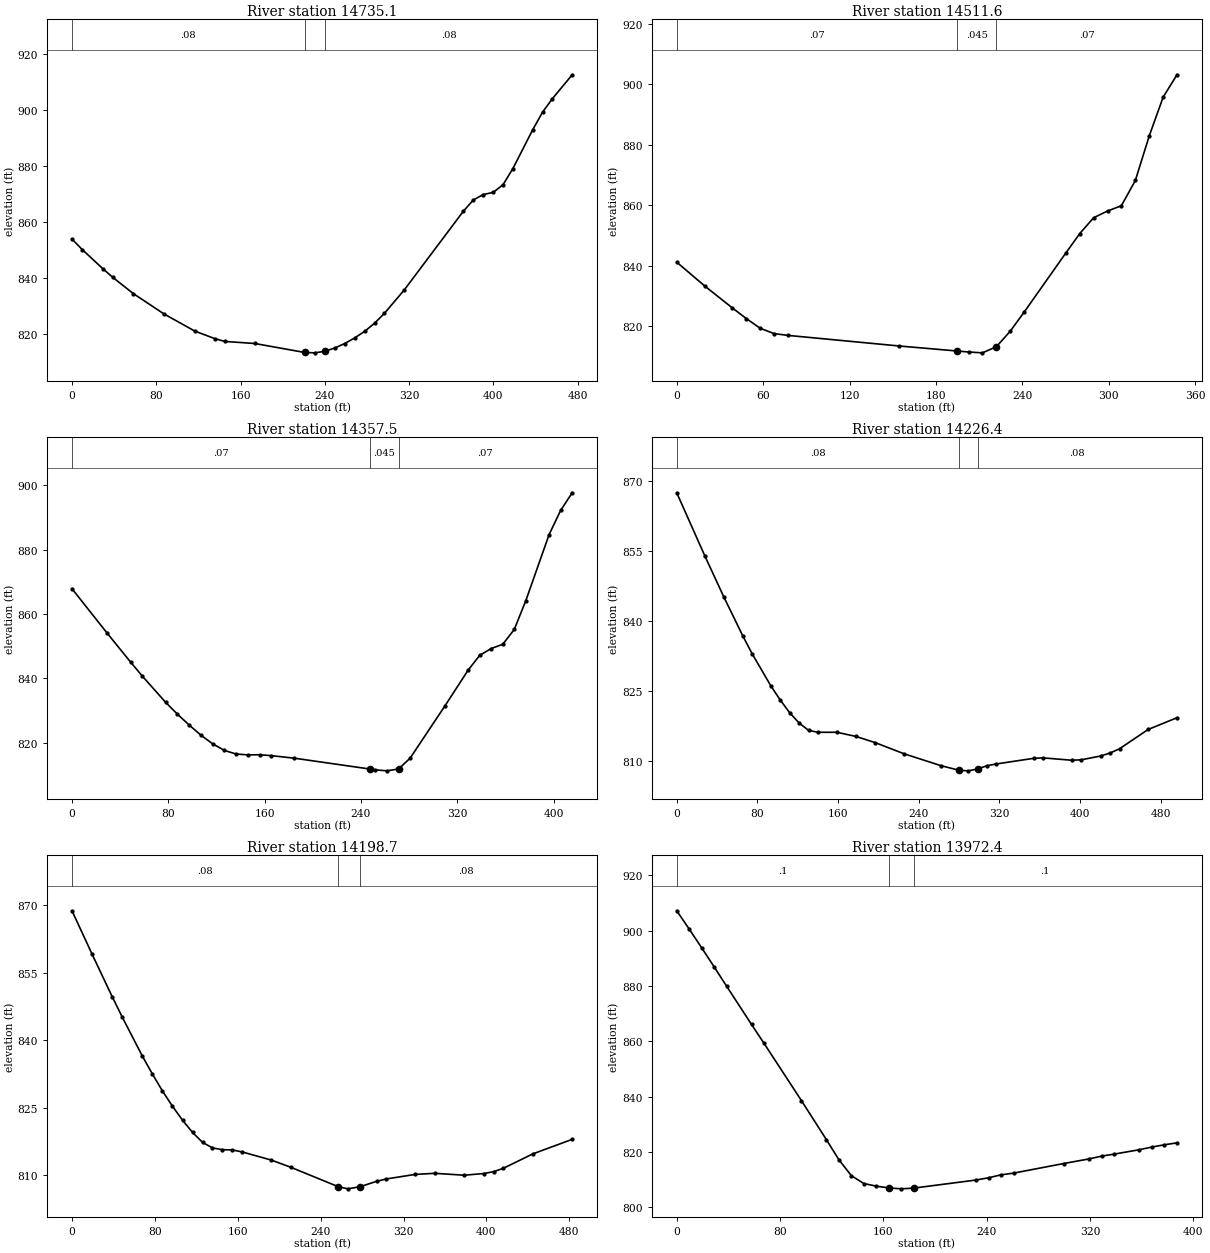
Type RM Length L Ch R = 1 ,14735.1 ,206.1,223.5,240.7
XS GIS Cut Line= 4
     1776332.006      459103.408     1776448.468      459101.071
     1776603.851      459057.408     1776788.951      459124.588
#Sta/Elev= 30
       0  853.99     9.7  850.26    29.1  843.47    38.8  840.29    58.2  834.53
    87.4  827.24   116.5  821.15   135.5  818.45     145  817.44   173.4  816.71
   220.9   813.5   230.4  813.37   239.9  813.91   249.4   815.1   258.9   816.7
   268.4  818.71   277.9  821.07   287.3  823.99   296.6  827.49   315.4  835.83
   371.6  863.99     381  867.96   390.4   869.9   399.8  870.65   409.2  873.44
   418.5  879.17   437.3  893.02   446.7  899.33     456  904.12   474.8  912.65
#Mann= 3 , 0 , 0
       0     .08       0   220.9    .045       0   239.9     .08       0
Bank Sta=220.9,239.9
XS Rating Curve= 0 ,0
Exp/Cntr=0.3,0.1

Type RM Length L Ch R = 1 ,14511.6 ,152.7,154.2,155.7
XS GIS Cut Line= 2
     1776360.479      459222.245     1776691.729      459327.106
#Sta/Elev= 23
       0  841.13    19.3   833.3    38.6     826    48.3  822.49    57.9  819.28
    67.6   817.5    77.2  816.91   154.4  813.41   194.6  811.75   202.7  811.42
   212.3  811.14     222  813.16   231.6  818.28   241.3  824.62   270.2  844.14
   279.9  850.57   289.5  855.81   299.2  858.04   308.8  859.78   318.5  868.13
   328.2  882.94   337.8  895.68   347.4  903.09
#Mann= 3 , 0 , 0
       0     .07       0   194.6    .045       0     222     .07       0
Bank Sta=194.6,222
XS Rating Curve= 0 ,0
Exp/Cntr=0.3,0.1

Type RM Length L Ch R = 1 ,14357.5 ,88.1,131,173.7
XS GIS Cut Line= 3
     1776286.453      459292.267     1776417.529      459393.395
     1776651.441      459481.445
#Sta/Elev= 30
       0  867.85    29.2  854.04    48.7  845.02    58.4  840.68    77.9  832.46
    87.6  828.83    97.4  825.42   107.1   822.3   116.9  819.59   126.6  817.55
   136.3  816.44   146.1  816.16   155.8   816.2   165.6  815.93   184.8  815.13
   247.7  811.75   252.1   811.5   261.7   811.2   271.3  811.79   280.9  815.16
   309.8  831.41     329   842.5   338.6   847.1   348.2  849.25   357.8  850.56
   367.4   855.2     377  864.18   396.3  884.69   405.9  892.22   415.5   897.7
#Mann= 3 , 0 , 0
       0     .07       0   247.7    .045       0   271.3     .07       0
Bank Sta=247.7,271.3
XS Rating Curve= 0 ,0
Exp/Cntr=0.3,0.1

Type RM Length L Ch R = 1 ,14226.4 ,27.7,27.7,27.7
XS GIS Cut Line= 5
     1776284.283      459300.079     1776411.178      459395.541
     1776438.378      459456.569     1776416.565      459563.817
     1776449.053      459721.616
#Sta/Elev= 30
       0  867.46      28  853.87    46.7  845.14    65.4  836.84    74.7  832.99
    93.4  826.05   102.8     823   112.1  820.29   121.4   818.1   130.8  816.53
   140.1  816.11   158.8  816.12   177.9  815.22     197  813.89   225.6   811.5
   262.1  808.96   280.3  807.96   289.4  807.85   298.6  808.27   307.7  808.94
   316.8  809.32     354  810.53   363.5  810.63   391.9  810.12   401.4  810.22
   420.4  811.03   429.8  811.66   439.3  812.59   467.7  816.73   496.2  819.23
#Mann= 3 , 0 , 0
       0     .08       0   280.3    .045       0   298.6     .08       0
Bank Sta=280.3,298.6
XS Rating Curve= 0 ,0
Exp/Cntr=0.3,0.1

Type RM Length L Ch R = 1 ,14198.7 ,276.7,226.3,175.7
XS GIS Cut Line= 5
      1776278.64       459306.59     1776379.562      459382.181
     1776411.766      459450.789     1776387.898      459568.144
     1776420.386      459725.944
#Sta/Elev= 30
       0  868.81    19.4  859.16    38.8  849.72    48.5  845.18    67.9  836.52
    77.6  832.53    87.3  828.77      97  825.36   106.7  822.26   116.4  819.54
   126.1  817.32   135.6  816.11     145  815.71   154.5  815.66     164  815.23
   192.4   813.4   211.1  811.81   257.2  807.47   266.4  807.01   278.3   807.5
     294  808.68   303.2   809.2   331.1  810.21   350.1  810.46   378.5  810.04
   397.5  810.41   406.9  810.83   416.4  811.58   444.8  814.78   482.8  818.01
#Mann= 3 , 0 , 0
       0     .08       0   257.2    .045       0   278.3     .08       0
Bank Sta=257.2,278.3
XS Rating Curve= 0 ,0
Exp/Cntr=0.3,0.1

Type RM Length L Ch R = 1 ,13972.4 ,184.8,184.5,183.9
XS GIS Cut Line= 3
     1776130.608      459637.695     1776379.219      459672.417
     1776428.524        459799.5
#Sta/Elev= 28
       0  907.17     9.6   900.6    19.3  893.79      29  886.88    38.6  879.92
    57.9  866.08    67.6  859.24    96.6  838.51   115.9  824.42   125.5  817.21
   135.2  811.42   144.8  808.58   154.5  807.62   164.1     807   173.8  806.65
   183.4  806.91   231.7  809.83   241.4  810.65     251   811.7   260.8  812.33
   299.7  815.81   319.2  817.46   328.9  818.48   338.6  819.19   358.1  820.79
   367.9  821.76   377.6  822.58   387.3  823.27
#Mann= 3 , 0 , 0
       0      .1       0   164.1    .045       0   183.4      .1       0
Bank Sta=164.1,183.4
XS Rating Curve= 0 ,0
Exp/Cntr=0.3,0.1

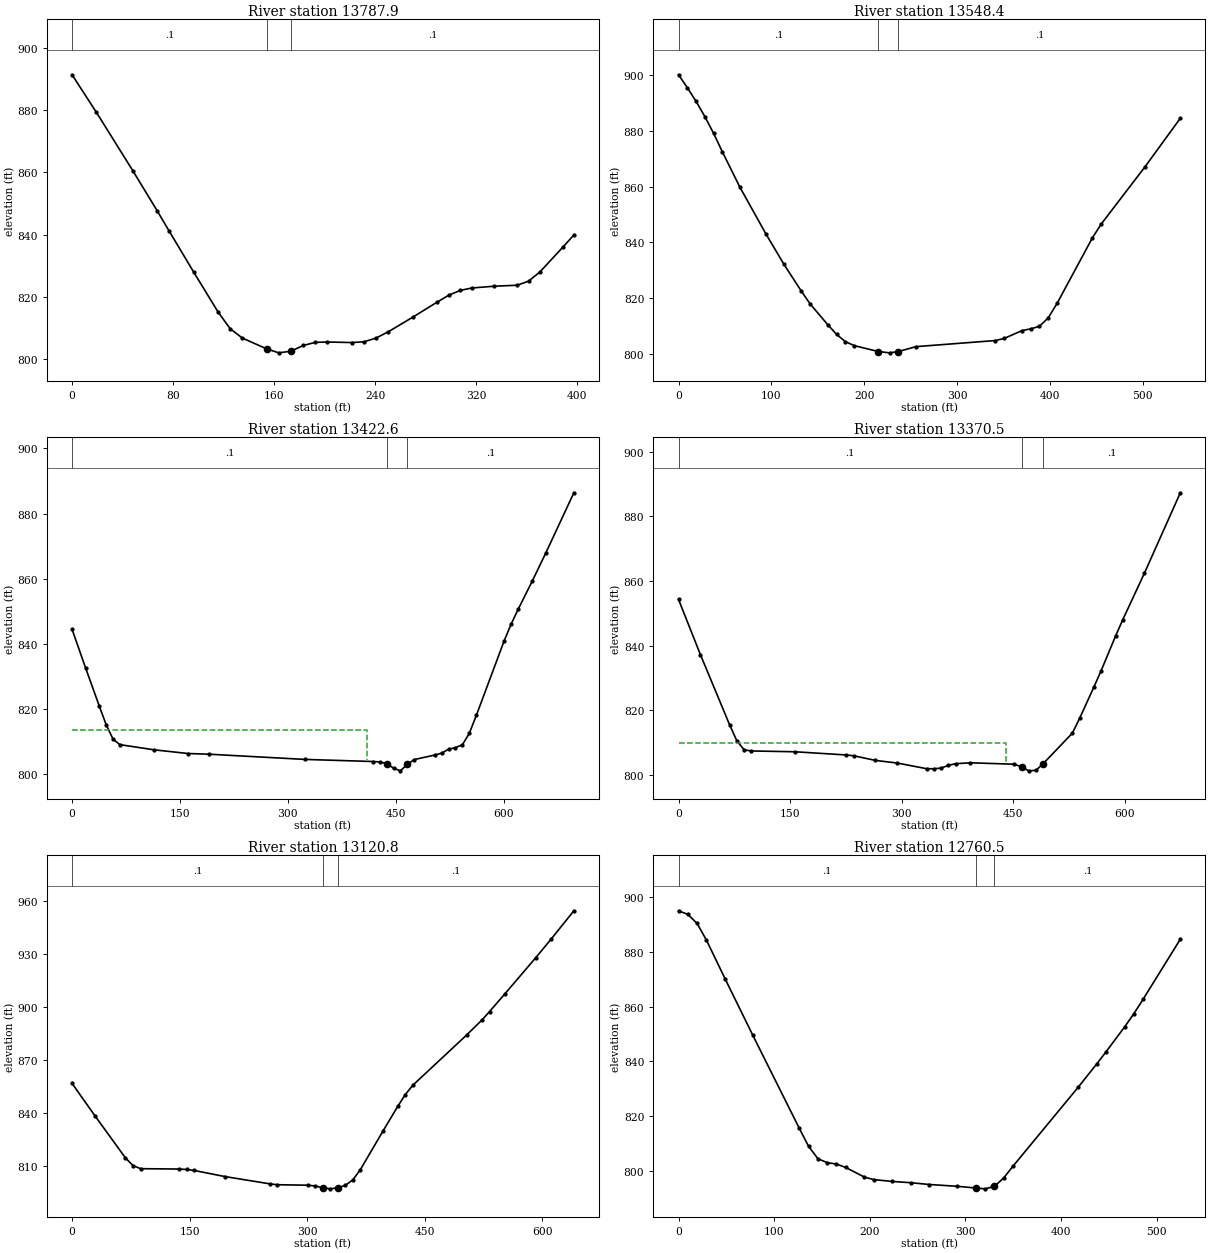
Type RM Length L Ch R = 1 ,13787.9 ,240,239.4,238.5
XS GIS Cut Line= 3
     1776105.318      459822.446     1776401.542      459859.338
     1776494.858      459891.891
#Sta/Elev= 30
       0  891.34    19.3  879.26    48.2  860.48    67.4  847.67      77  841.08
    96.3     828   115.6  815.18   125.2  809.82   134.8  806.83   154.1  803.35
   163.7  802.08   173.3  802.61     183  804.44   192.6  805.44   202.2  805.56
   221.5  805.38   231.1  805.62   240.7  806.83   250.4  808.85   269.6  813.49
   288.9  818.32   298.5  820.64   307.5  822.13   316.5   822.9   334.4  823.47
   352.4  823.78   361.4  825.08   370.4  828.04   388.4  835.92   397.3  839.92
#Mann= 3 , 0 , 0
       0      .1       0   154.1    .045       0   173.3      .1       0
Bank Sta=154.1,173.3
XS Rating Curve= 0 ,0
Exp/Cntr=0.3,0.1

Type RM Length L Ch R = 1 ,13548.4 ,153.2,125.8,93.6
XS GIS Cut Line= 4
     1776026.432      459964.212     1776128.394       460062.58
     1776345.877      460085.739     1776522.265      460122.545
#Sta/Elev= 30
       0  900.05     9.4  895.47    18.9  890.52    28.3  885.08    37.8  879.05
    47.2  872.44    66.1  859.77    94.4  842.86   113.3  832.26   132.2  822.55
   141.7  817.96   160.7   810.5   170.2  807.03   179.7  804.41   189.2  802.99
   215.1  800.87   227.3  800.39   236.8  800.86   255.8  802.61   341.4   804.8
   350.9  805.56   369.9  808.35   379.4  808.99   388.8   809.9   398.3  812.93
   407.8  818.11   445.7   841.5   455.2  846.47   502.6   867.1   540.6  884.46
#Mann= 3 , 0 , 0
       0      .1       0   215.1    .045       0   236.8      .1       0
Bank Sta=215.1,236.8
XS Rating Curve= 0 ,0
Exp/Cntr=0.3,0.1

Type RM Length L Ch R = 1 ,13422.6 ,57.8,52.1,51.3
XS GIS Cut Line= 4
     1775920.686      460384.666      1776153.61      460277.258
     1776338.772      460098.742      1776516.71      460145.462
#Sta/Elev= 30
       0   844.5      19  832.53      38  820.86    47.5  815.18      57   810.8
    66.5  809.12     114  807.53   161.5  806.39     190  806.19   323.2  804.59
   418.4  803.94     428  803.81   437.5  803.29     447  801.91   456.5  801.08
   466.1  803.06   475.6  804.53   504.2  805.92   513.7   806.5   523.4   807.7
   533.1   808.2   542.8   809.1   552.4  812.62   562.1  818.08   600.8  840.99
   610.5  846.11   620.2  850.63   639.6  859.19   658.9  868.02   697.7   886.4
#Mann= 3 , 0 , 0
       0      .1       0   437.5    .045       0   466.1      .1       0
#XS Ineff= 2 , 0
          410.48   813.5
Permanent Ineff=
       F       F
Bank Sta=437.5,466.1
XS Rating Curve= 0 ,0
Exp/Cntr=0.3,0.1

Type RM Length L Ch R = 1 ,13370.5 ,219.5,249.7,274.1
XS GIS Cut Line= 4
     1775924.159      460440.222     1776166.621      460333.703
     1776357.271      460149.897     1776496.571      460190.601
#Sta/Elev= 30
       0  854.29    29.4  837.23    68.7  815.48    78.5  810.51    88.3  807.73
    98.1   807.4   156.9  807.15   225.6  806.16   235.4  805.92   264.8  804.48
   294.2  803.66   333.5  801.92   343.3  801.88   353.1  802.11   362.9  802.94
   372.7  803.46   392.3  803.74   451.2   803.3   461.9  802.48   470.8  801.25
   480.6  801.41   490.4  803.48   529.6   812.9   539.3  817.47   558.7  827.24
   568.4  832.29   587.7  842.96   597.4  848.02   626.4  862.37   674.8   887.3
#Mann= 3 , 0 , 0
       0      .1       0   461.9    .045       0   490.4      .1       0
#XS Ineff= 2 , 0
          439.73  809.83
Permanent Ineff=
       F       F
Bank Sta=461.9,490.4
XS Rating Curve= 0 ,0
Exp/Cntr=0.3,0.1

Type RM Length L Ch R = 1 ,13120.8 ,369.8,360.3,350.4
XS GIS Cut Line= 4
     1775936.311      460499.249     1776136.912      460423.965
     1776357.593      460428.718     1776559.849      460392.265
#Sta/Elev= 30
       0  856.61    29.2  838.25    68.2  814.32    77.9  809.97    87.6  808.25
   136.4  808.05   146.1   807.8   155.8  807.25   194.8  803.81   252.6  799.63
   262.2  799.15   300.6  798.88   310.2  798.45   319.8  797.49   329.4  796.82
     339  797.36   348.6  798.77   358.2  801.82   367.8  807.57   396.6  829.41
   415.8  843.67   425.4  850.33     435  855.61   503.5  884.02   523.1  892.54
   532.9  897.39   552.4  907.39   591.6   927.8   611.2  938.32   640.5  954.54
#Mann= 3 , 0 , 0
       0      .1       0   319.8    .045       0     339      .1       0
Bank Sta=319.8,339
XS Rating Curve= 0 ,0
Exp/Cntr=0.3,0.1

Type RM Length L Ch R = 1 ,12760.5 ,278.1,273.9,269.1
XS GIS Cut Line= 2
      1775988.13      460879.304     1776489.432      460724.139
#Sta/Elev= 30
       0  895.01     9.7   893.7    19.4   890.4    29.2  884.28    48.6  870.24
    77.7  849.53   126.3  815.56     136     809   145.8  804.45   155.5  803.03
   165.2  802.51   174.9  801.26   194.4  797.75   204.1  796.84   223.5  796.16
     243   795.7   262.4  795.04   291.5  794.39     311  793.76   320.7  793.46
   330.4  794.38   340.1  797.45   349.8  801.73   417.9  830.54   437.3  839.05
     447  843.46   466.5  852.58   476.2  857.41   485.9  862.71   524.8  884.63
#Mann= 3 , 0 , 0
       0      .1       0     311    .045       0   330.4      .1       0
Bank Sta=311,330.4
XS Rating Curve= 0 ,0
Exp/Cntr=0.3,0.1

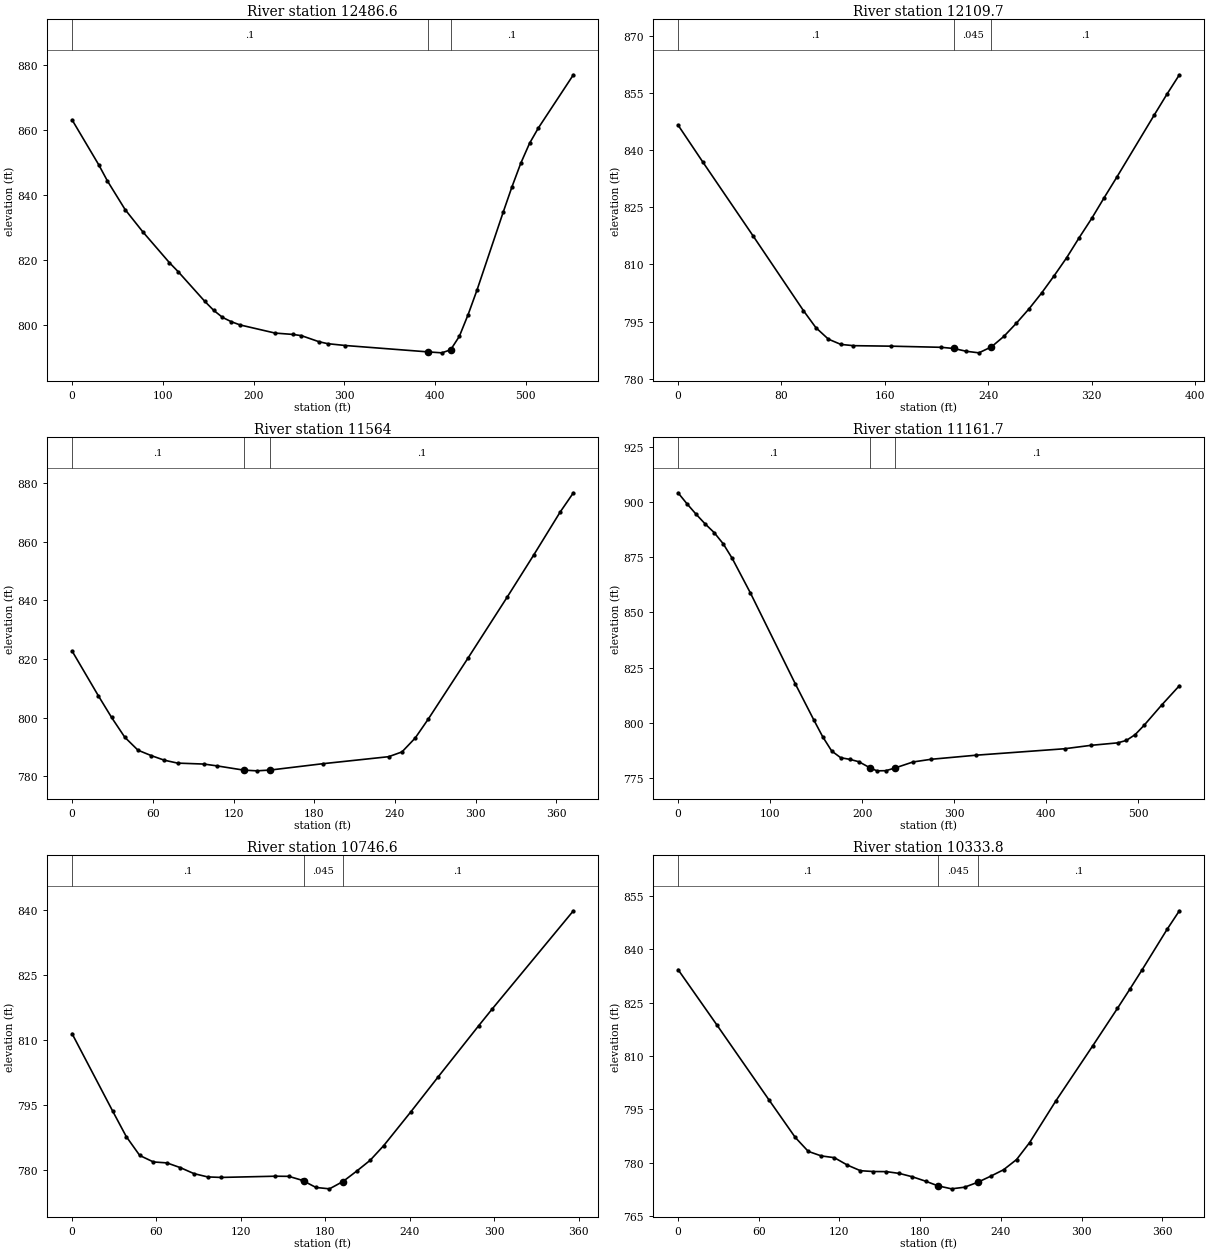
Type RM Length L Ch R = 1 ,12486.6 ,396.5,376.9,356.6
XS GIS Cut Line= 3
     1776092.884      461261.096     1776191.869      461128.034
     1776540.431      460960.684
#Sta/Elev= 30
       0  863.14    29.3  849.33      39  844.28    58.5  835.46      78   828.6
   107.3   819.1   117.1  816.28   146.3  807.17   156.1   804.4   165.8  802.23
   175.5   800.9   185.2   799.9   223.8  797.39   243.2  796.98   252.8   796.6
   272.2  794.72   281.8  794.12   301.2  793.56   391.9   791.6   407.5   791.3
   417.2  792.24   426.8  796.38   436.5   803.1   446.2  810.59   475.2  834.72
   484.8  842.47   494.5  849.74   504.2   855.9   513.8  860.58   552.5  877.02
#Mann= 3 , 0 , 0
       0      .1       0   391.9    .045       0   417.2      .1       0
Bank Sta=391.9,417.2
XS Rating Curve= 0 ,0
Exp/Cntr=0.3,0.1

Type RM Length L Ch R = 1 ,12109.7 ,547.7,545.7,542.3
XS GIS Cut Line= 2
     1776514.788      461536.956     1776688.375      461190.159
#Sta/Elev= 27
       0  846.57    19.4  836.76    58.2  817.42      97  797.89   106.6  793.43
   116.3   790.4     126  789.02   135.7  788.69   164.8  788.56   203.6  788.26
   213.3  787.95     223  787.22   232.7  786.81   242.4  788.37   252.1  791.14
   261.8  794.62   271.5  798.35   281.2  802.49   290.9  807.02   300.6  811.76
   310.2  816.97     320  822.08   329.6   827.5   339.3  832.84   368.4  849.23
   378.1  854.62   387.8  859.76
#Mann= 3 , 0 , 0
       0      .1       0   213.3    .045       0   242.4      .1       0
Bank Sta=213.3,242.4
XS Rating Curve= 0 ,0
Exp/Cntr=0.3,0.1

Type RM Length L Ch R = 1 ,11564   ,382.4,402.3,420
XS GIS Cut Line= 2
      1777010.16      461676.738     1777144.274      461329.082
#Sta/Elev= 23
       0  822.76    19.6  807.42    29.4  800.05    39.2   793.3      49  788.88
    58.8  787.04    68.6  785.46    78.4  784.47    98.1  784.14   107.9  783.51
   127.5  782.08   137.3  781.83   147.1  782.09   186.3  784.26   235.3  786.66
   245.2  788.29     255  793.02   264.8  799.54   294.2  820.27   323.6  841.29
   343.2  855.58   362.8  870.21   372.6  876.76
#Mann= 3 , 0 , 0
       0      .1       0   127.5    .045       0   147.1      .1       0
Bank Sta=127.5,147.1
XS Rating Curve= 0 ,0
Exp/Cntr=0.3,0.1

Type RM Length L Ch R = 1 ,11161.7 ,408.6,415,419.5
XS GIS Cut Line= 3
     1777162.373      461893.014      1777429.04      461708.987
     1777624.179      461606.209
#Sta/Elev= 30
       0  904.15     9.8  899.14    19.6  894.46    29.4  890.09    39.3  886.11
    49.1  881.05    58.9  874.43    78.6  858.82   127.6  817.49   147.3  801.49
   157.1  793.75   166.9  787.27   176.7  784.22   186.6  783.48   196.4  782.41
     208  779.77     216  778.28   225.8  778.35   235.6  779.56   255.3   782.3
   274.9  783.51     324  785.37   419.9  788.28   448.7  789.83   477.4  790.94
     487  792.04   496.6  794.69   506.2  798.86   525.4  808.08   544.6  816.82
#Mann= 3 , 0 , 0
       0      .1       0     208    .045       0   235.6      .1       0
Bank Sta=208,235.6
XS Rating Curve= 0 ,0
Exp/Cntr=0.3,0.1

Type RM Length L Ch R = 1 ,10746.6 ,403.8,412.8,420.9
XS GIS Cut Line= 2
     1777409.634      462156.721     1777726.788      461994.585
#Sta/Elev= 25
       0  811.52    28.9  793.64    38.5   787.8    48.1  783.43    57.8  781.94
    67.4  781.72      77  780.62    86.6  779.25    96.3  778.49   105.9  778.37
   144.4  778.65     154  778.62   163.7  777.69   164.5  777.55   173.3  776.06
   182.9  775.74   192.5  777.43   202.2  779.82   211.8  782.32   221.4  785.69
   240.7  793.49   259.9  801.46   288.8   813.3   298.4  817.16   356.2  839.84
#Mann= 3 , 0 , 0
       0      .1       0   164.5    .045       0   192.5      .1       0
Bank Sta=164.5,192.5
XS Rating Curve= 0 ,0
Exp/Cntr=0.3,0.1

Type RM Length L Ch R = 1 ,10333.8 ,242,237.8,233.6
XS GIS Cut Line= 3
     1777453.736      462484.725     1777730.429      462436.981
     1777815.064      462401.174
#Sta/Elev= 29
       0  834.33      29  818.68    67.8  797.56    87.1  787.13    96.8  783.18
   106.5   781.9   116.2  781.41   125.9  779.32   135.6  777.74   145.2  777.51
   154.9  777.48   164.6  776.97   174.3  776.02     184   774.8   193.1   773.5
   203.3  772.64     213   773.1   222.7  774.47   232.4  776.19     242  778.01
   251.7  780.89   261.4  785.67   280.8  797.34   308.4  812.93   326.7  823.43
   335.9  828.82   345.1  834.32   363.5   845.6   372.7  850.86
#Mann= 3 , 0 , 0
       0      .1       0   193.1    .045       0   222.7      .1       0
Bank Sta=193.1,222.7
XS Rating Curve= 0 ,0
Exp/Cntr=0.3,0.1

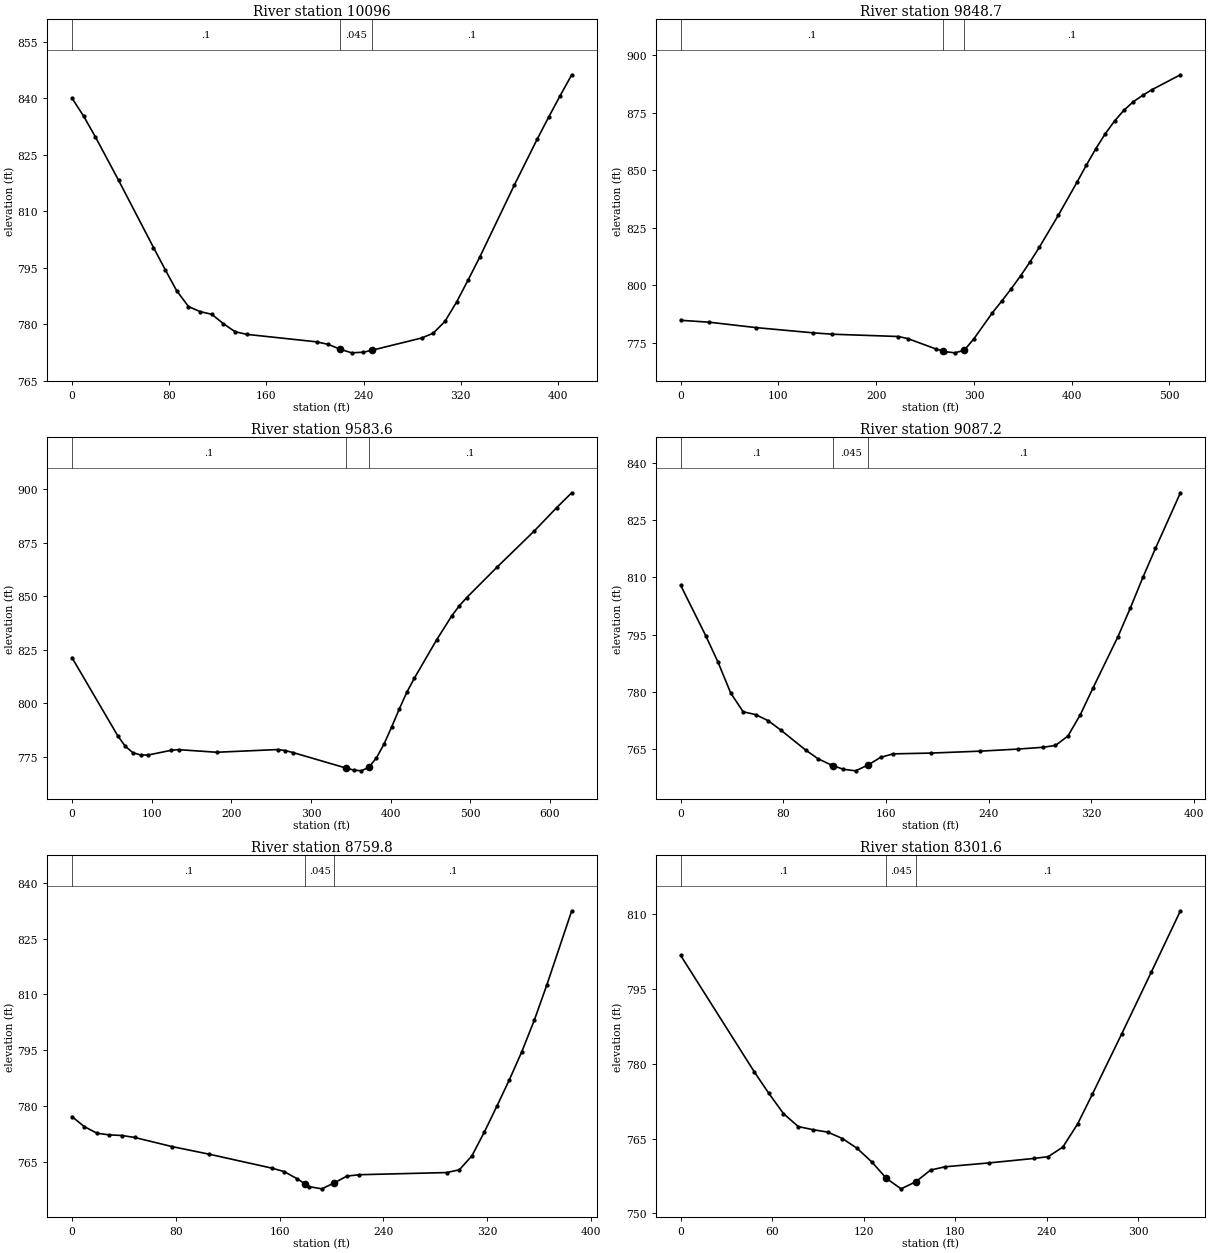
Type RM Length L Ch R = 1 ,10096   ,259.9,247.3,234.7
XS GIS Cut Line= 3
     1777488.066      462751.005     1777806.712      462645.374
     1777869.711      462603.643
#Sta/Elev= 30
       0  840.06     9.6  835.27    19.2   829.8    38.4   818.2    67.1  800.36
    76.7  794.49    86.3  788.81    95.9  784.68   105.5  783.32   115.1  782.61
   124.7  780.09   134.3  777.97   143.9  777.28   201.4  775.29     211  774.61
   220.6  773.34   230.2  772.37   239.8  772.54   247.3  773.09   287.7  776.31
   297.3  777.58   306.9   780.7   316.5  785.84   326.1  791.77   335.7  797.87
     364  816.91   382.9  829.16   392.4  835.05   401.8  840.72   411.3  846.26
#Mann= 3 , 0 , 0
       0      .1       0   220.6    .045       0   247.3      .1       0
Bank Sta=220.6,247.3
XS Rating Curve= 0 ,0
Exp/Cntr=0.3,0.1

Type RM Length L Ch R = 1 ,9848.7  ,245.2,265.1,284.5
XS GIS Cut Line= 3
     1777638.198      462995.792     1777825.915      462894.881
     1778047.269      462695.228
#Sta/Elev= 30
       0  784.78    29.1  783.96    77.5  781.59   135.6  779.33     155  778.74
   222.7  777.74   232.4  776.82   261.2  772.31     268   771.5   270.8  771.16
   280.4  770.64     290  771.74   299.7  776.61   318.9  788.07   328.5  793.19
   338.1  798.48   347.7   804.1   357.4  810.18     367  816.62   386.2  830.37
   405.4   844.8     415  852.25   424.7   859.4   434.3  865.86   443.9  871.44
   453.5  876.12   463.1  879.81   472.8  882.62   482.4   885.1   511.2   891.5
#Mann= 3 , 0 , 0
       0      .1       0     268    .045       0     290      .1       0
Bank Sta=268,290
XS Rating Curve= 0 ,0
Exp/Cntr=0.3,0.1

Type RM Length L Ch R = 1 ,9583.6  ,521,496.4,469
XS GIS Cut Line= 4
     1777678.346      463230.167     1777882.339      463088.023
      1778062.46      463069.577     1778252.347      463015.323
#Sta/Elev= 30
       0   821.3    57.4  784.75    66.9  779.81    76.5  776.81    86.1  775.74
    95.6  775.72   124.3  777.91   133.9  778.23   181.7  777.01   258.2  778.28
   267.7  777.81   277.2  776.89   343.9  769.63   353.5  768.69     363  768.32
   372.5  769.95     382   774.3   391.6  780.83   401.1  788.73   410.6  797.12
   420.2  805.03   429.7  811.68   457.9  829.75   476.7  840.83   486.1  845.51
   495.5  849.41   533.1  863.47   580.2  880.53   608.4  891.48   627.2   898.4
#Mann= 3 , 0 , 0
       0      .1       0   343.9    .045       0   372.5      .1       0
Bank Sta=343.9,372.5
XS Rating Curve= 0 ,0
Exp/Cntr=0.3,0.1

Type RM Length L Ch R = 1 ,9087.2  ,329.7,327.4,321.5
XS GIS Cut Line= 2
     1778050.524      463568.709     1778310.941      463278.995
#Sta/Elev= 30
       0   807.9    19.5  794.76    29.2  787.75      39  779.75    48.7  774.85
    58.4   774.1    68.2  772.52    77.9   770.1    97.4  764.84   107.1  762.56
   116.9  761.01   118.7  760.79   126.6  759.82   136.3   759.4   146.1  760.92
   155.8  762.92   165.6  763.84   194.8  764.04   233.7  764.55     263  765.09
   282.4  765.56   292.2  766.04   301.9   768.5   311.6   774.1   321.4  781.04
   340.9  794.48   350.6  802.02   360.3  809.95   370.1  817.54   389.6   832.1
#Mann= 3 , 0 , 0
       0      .1       0   118.7    .045       0   146.1      .1       0
Bank Sta=118.7,146.1
XS Rating Curve= 0 ,0
Exp/Cntr=0.3,0.1

Type RM Length L Ch R = 1 ,8759.8  ,473.2,458.2,442.5
XS GIS Cut Line= 2
      1778295.43      463743.181     1778491.573      463411.602
#Sta/Elev= 27
       0  777.13     9.6  774.42    19.3  772.66    28.9  772.21    38.5  772.05
    48.2  771.53      77  769.08   105.9  767.01   154.1  763.27   163.7  762.32
   173.4  760.45     180  758.96     183  758.28   192.6   757.7   202.3  759.33
   211.9  761.13   221.5   761.5   288.9  762.08   298.6  762.83   308.2  766.55
   317.8  772.94   327.5  779.92   337.1  787.03   346.7  794.57   356.4  803.11
     366  812.54   385.2  832.51
#Mann= 3 , 0 , 0
       0      .1       0     180    .045       0   202.3      .1       0
Bank Sta=180,202.3
XS Rating Curve= 0 ,0
Exp/Cntr=0.3,0.1

Type RM Length L Ch R = 1 ,8301.6  ,365.7,382.8,393.6
XS GIS Cut Line= 2
     1778803.072      463915.199     1778811.366      463587.674
#Sta/Elev= 24
       0  801.67    48.2  778.38    57.8  774.04    67.4  769.99    77.1  767.39
    86.7  766.77    96.4  766.28     106     765   115.6  763.05   125.3   760.3
   134.9     757   144.5  754.92   154.2  756.35   163.8  758.68   173.4  759.34
   202.4  760.12   231.3     761   240.9  761.36   250.5  763.28   260.2  767.91
   269.8  773.83   289.1  785.95   308.4  798.26   327.6  810.61
#Mann= 3 , 0 , 0
       0      .1       0   134.9    .045       0   154.2      .1       0
Bank Sta=134.9,154.2
XS Rating Curve= 0 ,0
Exp/Cntr=0.3,0.1

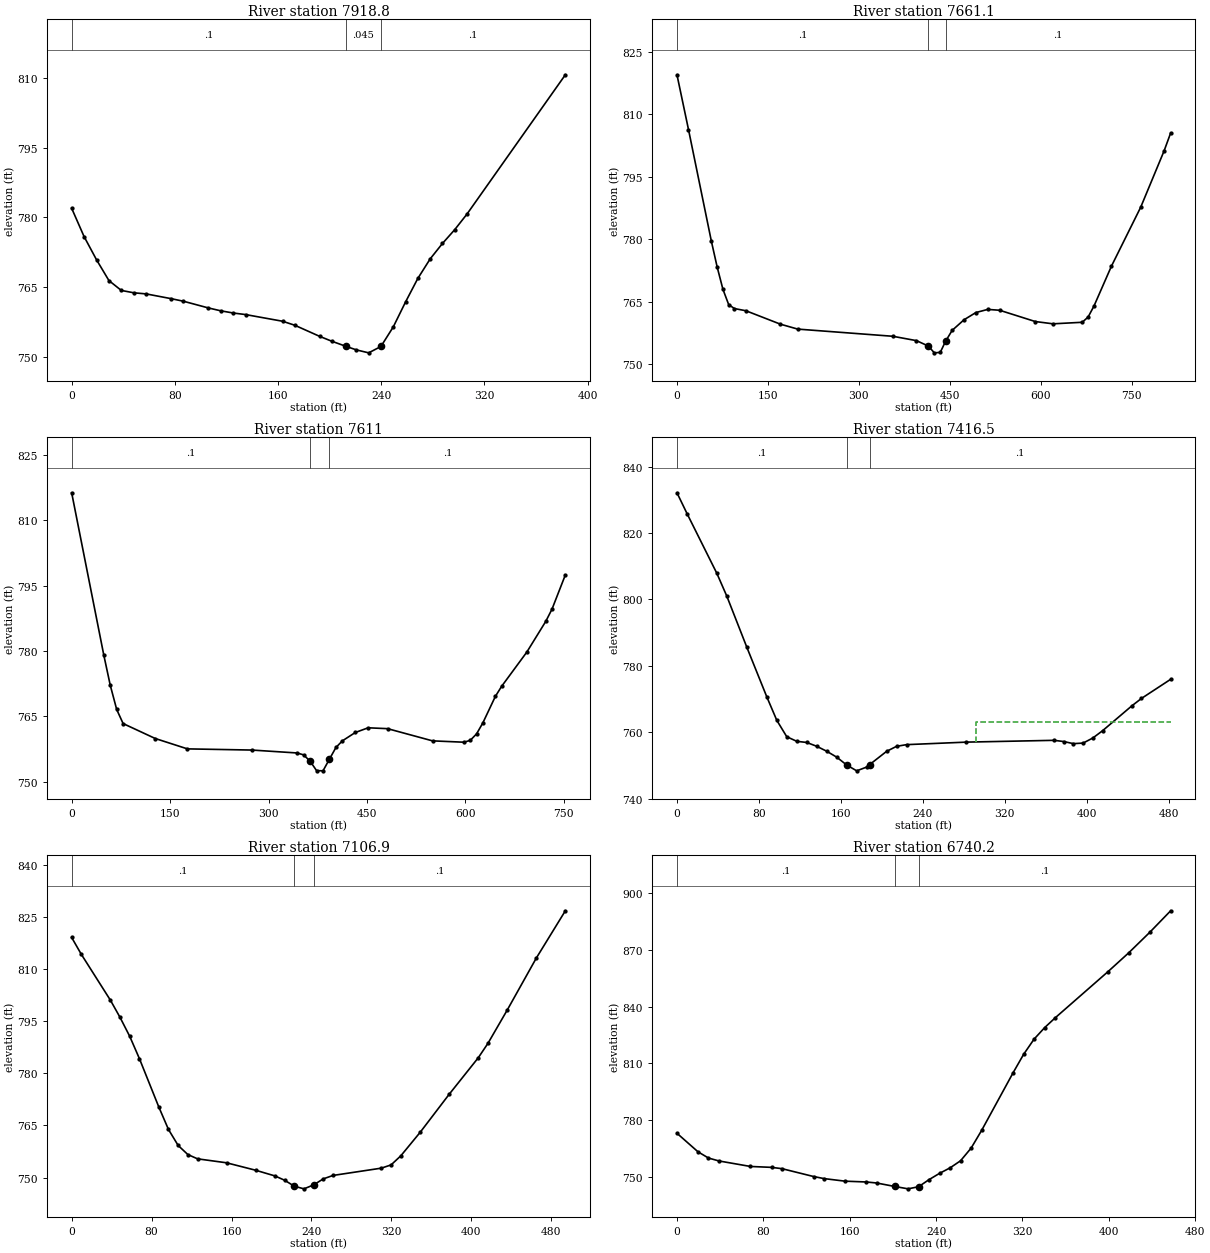
Type RM Length L Ch R = 1 ,7918.8  ,164.5,257.7,298.9
XS GIS Cut Line= 3
     1778992.066      463973.239     1779104.913      463882.961
     1779178.698      463656.399
#Sta/Elev= 29
       0  781.93     9.6  775.85    19.3  770.83    28.9  766.36    38.5  764.24
    48.2  763.73    57.8  763.49    77.1  762.47    86.7  761.91     106  760.47
   115.6  759.85   125.2  759.38   134.9  759.04   163.6   757.6   173.1  756.73
   192.2  754.36   201.7   753.3   212.6  752.21   220.8  751.43   230.3   750.8
   239.8  752.17   249.4   756.4   258.9  761.76   268.4  766.82     278  771.04
   287.5  774.35     297  777.32   306.5  780.67   382.8  810.68
#Mann= 3 , 0 , 0
       0      .1       0   212.6    .045       0   239.8      .1       0
Bank Sta=212.6,239.8
XS Rating Curve= 0 ,0
Exp/Cntr=0.3,0.1

Type RM Length L Ch R = 1 ,7661.1  ,104,50.1,49.4
XS GIS Cut Line= 5
     1778973.837      464023.586     1779116.249       463898.63
     1779545.885      463929.836     1779719.835      463846.698
     1779721.009      463846.773
#Sta/Elev= 30
       0   819.5      19  806.35    56.8  779.48    66.3  773.32    75.8  767.97
    85.3  764.29    94.7  763.35   113.7  762.82   170.5   759.6   199.2  758.41
   355.9  756.69     395  755.64   414.6  754.34   424.4  752.71   434.2  752.81
   442.9  755.46   453.8   758.1   473.4  760.65     493  762.39   512.5  763.14
   532.1  762.94   590.9  760.23   620.2  759.68   668.4  760.05   678.1  761.32
   687.7  763.94   716.6  773.55   764.8  787.69   803.4  801.23   814.2  805.52
#Mann= 3 , 0 , 0
       0      .1       0   414.6    .045       0   442.9      .1       0
Bank Sta=414.6,442.9
XS Rating Curve= 0 ,0
Exp/Cntr=0.3,0.1

Type RM Length L Ch R = 1 ,7611    ,213.2,194.6,174.8
XS GIS Cut Line= 5
     1779013.287      464041.526     1779126.953      463948.403
     1779519.438      463975.542     1779713.653      463893.743
     1779714.828      463893.813
#Sta/Elev= 30
       0   816.3      49  779.02    58.8  772.13    68.6  766.57    78.4  763.33
   127.4   759.9   176.4  757.52   274.8  757.25   343.6  756.58   353.5  756.14
   363.3   754.7   373.2  752.53     383  752.48   392.8  755.16   402.7  757.84
   412.5  759.36   432.2  761.28   451.8  762.36   481.4  762.16   549.9  759.36
   597.8  759.05   607.4  759.48     617  760.96   626.6  763.49   645.7  769.58
   655.3   771.9   693.6  779.74   722.4  786.77   731.9  789.57   752.3  797.45
#Mann= 3 , 0 , 0
       0      .1       0   363.3    .045       0   392.8      .1       0
Bank Sta=363.3,392.8
XS Rating Curve= 0 ,0
Exp/Cntr=0.3,0.1

Type RM Length L Ch R = 1 ,7416.5  ,303.1,309.6,316
XS GIS Cut Line= 3
     1779242.997      464248.779     1779481.476      464096.999
      1779671.69      464037.108
#Sta/Elev= 30
       0  832.12     9.8  825.87      39  807.82    48.7  800.97    68.2  785.61
    87.7  770.67    97.5  763.58   107.2  758.65     117  757.26   126.7  756.92
   136.5  755.76   146.2  754.28     156  752.49   165.7  750.14   175.5  748.37
   185.2   749.5   188.2  750.26   204.7  754.24   214.4  755.75   224.2  756.26
   282.7  757.02   368.2  757.56   377.6   757.2   387.1  756.56   396.6  756.73
   406.1  758.26   415.6  760.45   444.1  767.92   453.6  770.18   482.1  775.94
#Mann= 3 , 0 , 0
       0      .1       0   165.7    .045       0   188.2      .1       0
#XS Ineff= 2 , 0
                          291.78             763
Permanent Ineff=
       F       F
Bank Sta=165.7,188.2
XS Rating Curve= 0 ,0
Exp/Cntr=0.3,0.1

Type RM Length L Ch R = 1 ,7106.9  ,368,366.7,365
XS GIS Cut Line= 2
     1779345.243      464481.132     1779809.327      464311.546
#Sta/Elev= 30
       0  819.14     9.7  814.27    38.8  801.07    48.4  796.14    58.1  790.68
    67.8  784.26    87.2  770.34    96.9  763.85   106.6  759.24   116.3  756.63
     126   755.4     155  754.26   184.1  752.12   203.4  750.48   213.1  749.24
   222.8  747.52   232.5  746.76   242.2   747.9   251.9  749.64   261.6  750.62
     310  752.72   319.7  753.66   329.4  756.26   348.8  763.04   377.8  773.98
   406.9  784.49   416.6  788.64     436  798.28     465   813.2   494.1  826.83
#Mann= 3 , 0 , 0
       0      .1       0   222.8    .045       0   242.2      .1       0
Bank Sta=222.8,242.2
XS Rating Curve= 0 ,0
Exp/Cntr=0.3,0.1

Type RM Length L Ch R = 1 ,6740.2  ,298.8,300.2,301.6
XS GIS Cut Line= 2
     1779537.797      464773.575     1779959.013      464595.414
#Sta/Elev= 30
       0  772.94    19.5  763.11    29.2  759.81    38.9  758.27    68.1  755.35
    87.6  754.88    97.3  754.18   126.5  750.03   136.2  748.93   155.7  747.56
   175.2  747.14   184.9   746.6   201.7  744.76   214.1   743.5   223.8  744.62
   233.5  748.38   243.3  751.73     253  754.62   262.7  758.38   272.5   765.1
   282.2  774.45   311.4  805.04   321.1  814.75   330.8  822.82   340.6  828.91
   350.3  834.07     399  858.43   418.4   868.5   437.9  879.36   457.3   890.8
#Mann= 3 , 0 , 0
       0      .1       0   201.7    .045       0   223.8      .1       0
Bank Sta=201.7,223.8
XS Rating Curve= 0 ,0
Exp/Cntr=0.3,0.1

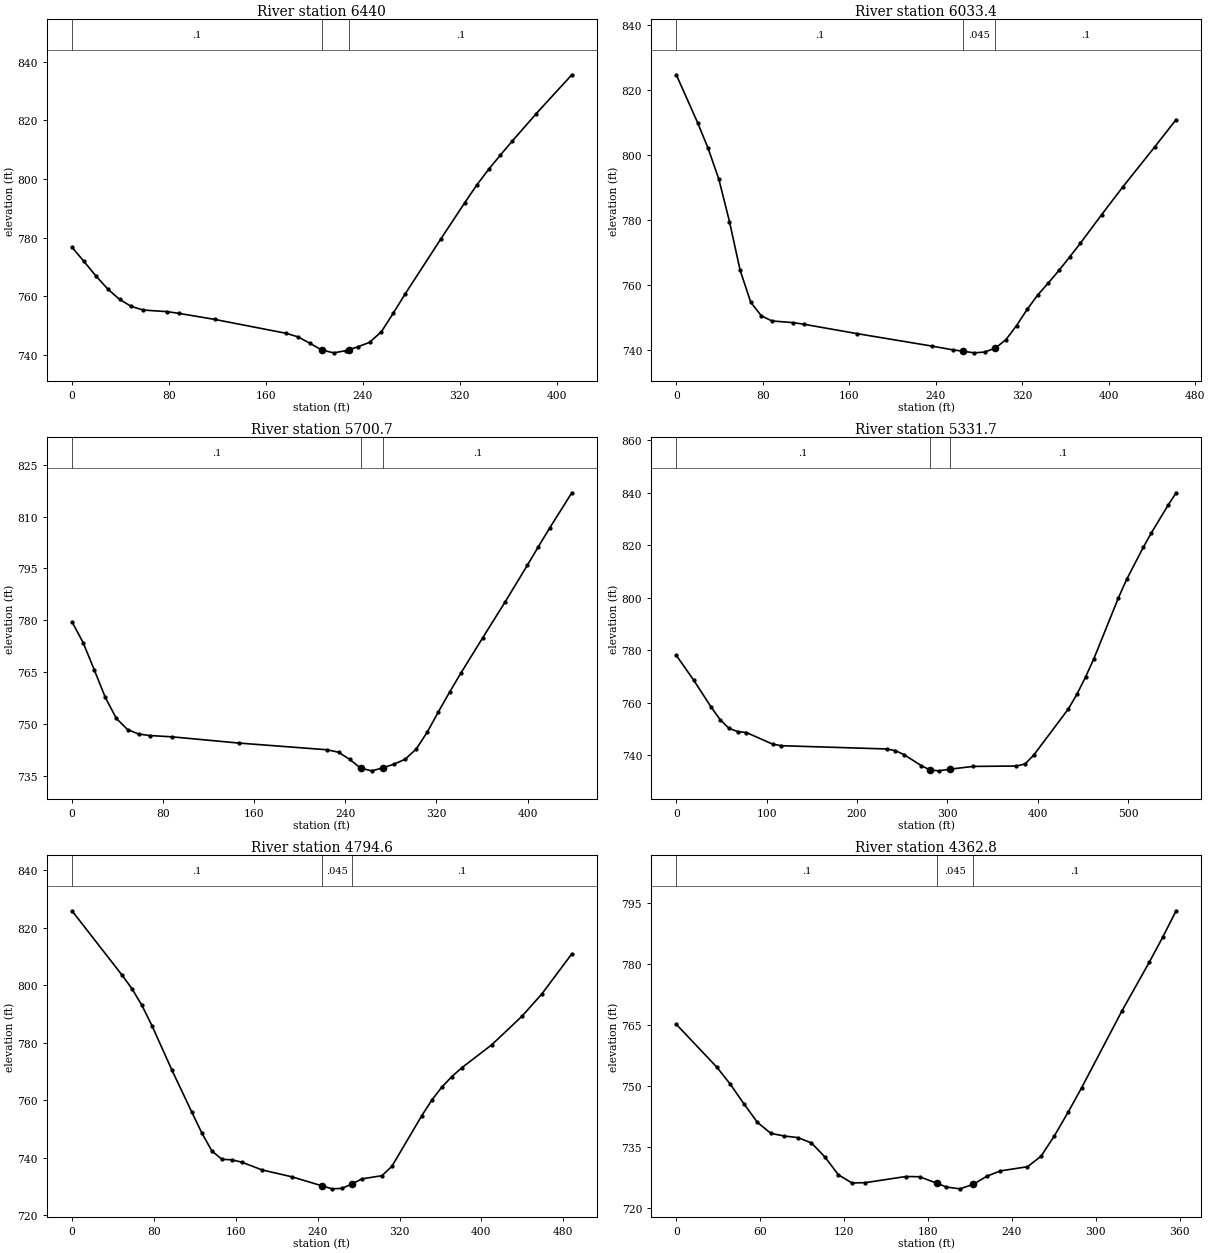
Type RM Length L Ch R = 1 ,6440    ,396,406.6,417.1
XS GIS Cut Line= 2
     1779603.222      465054.937     1779989.941      464911.708
#Sta/Elev= 30
       0   776.7     9.8  771.88    19.6  766.95    29.5  762.42    39.3  758.86
    49.1  756.45    58.9  755.23    78.6  754.69    88.4  754.09   117.8  752.03
   176.7  747.29   186.6  746.06   196.4  743.87   206.2  741.56     216  740.62
   225.8  741.35   228.5  741.71   235.6  742.64   245.5  744.19   255.3  747.84
   265.1  754.16   274.9  760.74   304.4  779.56     324  791.84   333.8  797.82
   343.7  803.24   353.5  808.18   363.3  812.95   382.9  822.24   412.4  835.58
#Mann= 3 , 0 , 0
       0      .1       0   206.2    .045       0   228.5      .1       0
Bank Sta=206.2,228.5
XS Rating Curve= 0 ,0
Exp/Cntr=0.3,0.1

Type RM Length L Ch R = 1 ,6033.4  ,331.6,332.6,333.2
XS GIS Cut Line= 2
     1779624.022      465367.743     1780086.403      465364.006
#Sta/Elev= 30
       0  824.82    19.7   810.1    29.5  802.14    39.4  792.65    49.2  779.66
      59  764.74    68.9   754.8    78.7  750.66    88.5  749.08   108.2  748.56
   118.1  748.06   167.2  745.18   236.1  741.37   255.8  740.19   265.6  739.75
   275.5  739.27   285.3  739.51   295.2  740.74     305  743.33   314.8  747.67
   324.7  752.69   334.5  757.14   344.3   760.8   354.2  764.71     364   768.8
   373.8  772.98   393.5  781.79   413.2  790.38   442.7  802.67   462.4  811.04
#Mann= 3 , 0 , 0
       0      .1       0   265.6    .045       0   295.2      .1       0
Bank Sta=265.6,295.2
XS Rating Curve= 0 ,0
Exp/Cntr=0.3,0.1

Type RM Length L Ch R = 1 ,5700.7  ,387.7,369.1,349.6
XS GIS Cut Line= 2
     1779631.209      465683.754     1780070.073        465685.8
#Sta/Elev= 29
       0  779.55     9.8   773.5    19.5  765.69    29.3  757.62      39  751.54
    48.8  748.35    58.5  747.04    68.3   746.6    87.8  746.23   146.3  744.43
   224.3  742.47   234.1  741.76   243.8  739.71   253.6  737.13   263.3  736.38
   273.1  737.26   282.8  738.32   292.6  739.75   302.3   742.7   312.1  747.66
   321.8  753.49   331.6  759.18   341.3  764.58   360.8  774.99   380.4  785.33
   399.9  795.92   409.6  801.33   419.4  806.66   438.9   816.9
#Mann= 3 , 0 , 0
       0      .1       0   253.6    .045       0   273.1      .1       0
Bank Sta=253.6,273.1
XS Rating Curve= 0 ,0
Exp/Cntr=0.3,0.1

Type RM Length L Ch R = 1 ,5331.7  ,535,537.1,527.5
XS GIS Cut Line= 4
     1779713.048      466243.332     1779847.061      466053.055
     1780024.016      465922.081     1780083.372      465841.295
#Sta/Elev= 30
       0   778.1    19.4  768.58    38.8  758.26    48.5  753.63    58.2  750.33
    67.9  749.06    77.6   748.7   106.7  744.28   116.4  743.69   232.7  742.45
   242.3  741.82   251.9  740.32     271  736.12   280.6  734.48   290.2  734.12
   302.4  734.73   328.4  735.81   376.3  735.95   385.9  736.75   395.4  740.06
   433.7  757.63   443.3  763.28   452.9  769.88     462  776.76   489.3  800.06
   498.4  807.07   516.7  819.21   525.8   824.8     544  835.17   553.1  840.01
#Mann= 3 , 0 , 0
       0      .1       0   280.6    .045       0   302.4      .1       0
Bank Sta=280.6,302.4
XS Rating Curve= 0 ,0
Exp/Cntr=0.3,0.1

Type RM Length L Ch R = 1 ,4794.6  ,440.8,431.8,422.9
XS GIS Cut Line= 2
     1779975.068      466530.933     1780317.506      466182.836
#Sta/Elev= 30
       0  825.97    48.8  803.64    58.6  798.85    68.4  793.01    78.1  786.02
    97.7  770.48   117.2  755.81     127  748.55   136.7  742.38   146.5  739.49
   156.3   739.3     166  738.48   185.6   735.8   214.8   733.4   244.2  730.26
   253.9  729.21   263.7  729.37   273.4  730.89   283.2  732.67   302.8  733.79
   312.5  737.02   341.8  754.71   351.6  760.11   361.3  764.61   371.1  768.27
   380.9  771.36   410.2  779.37   439.5  789.24     459  797.01   488.3  810.99
#Mann= 3 , 0 , 0
       0      .1       0   244.2    .045       0   273.4      .1       0
Bank Sta=244.2,273.4
XS Rating Curve= 0 ,0
Exp/Cntr=0.3,0.1

Type RM Length L Ch R = 1 ,4362.8  ,403.9,389.3,374.2
XS GIS Cut Line= 2
      1780403.28      466777.837     1780568.611      466461.003
#Sta/Elev= 30
       0  765.15      29  754.62    38.6  750.44    48.3  745.64      58  741.07
    67.6  738.36    77.3   737.7    86.9  737.32    96.6  736.02   106.2  732.58
   115.9  728.18   125.6  726.17   135.2  726.25   164.2  727.76   173.9   727.7
   186.4   726.1   193.2  725.17   202.8  724.73   212.5  725.86   222.2  727.86
   231.8  729.14   251.1  730.16   260.8  732.74   270.4  737.78   280.1  743.52
   289.8  749.55   318.7  768.47   338.1  780.35   347.7  786.49   357.4  793.04
#Mann= 3 , 0 , 0
       0      .1       0   186.4    .045       0   212.5      .1       0
Bank Sta=186.4,212.5
XS Rating Curve= 0 ,0
Exp/Cntr=0.3,0.1