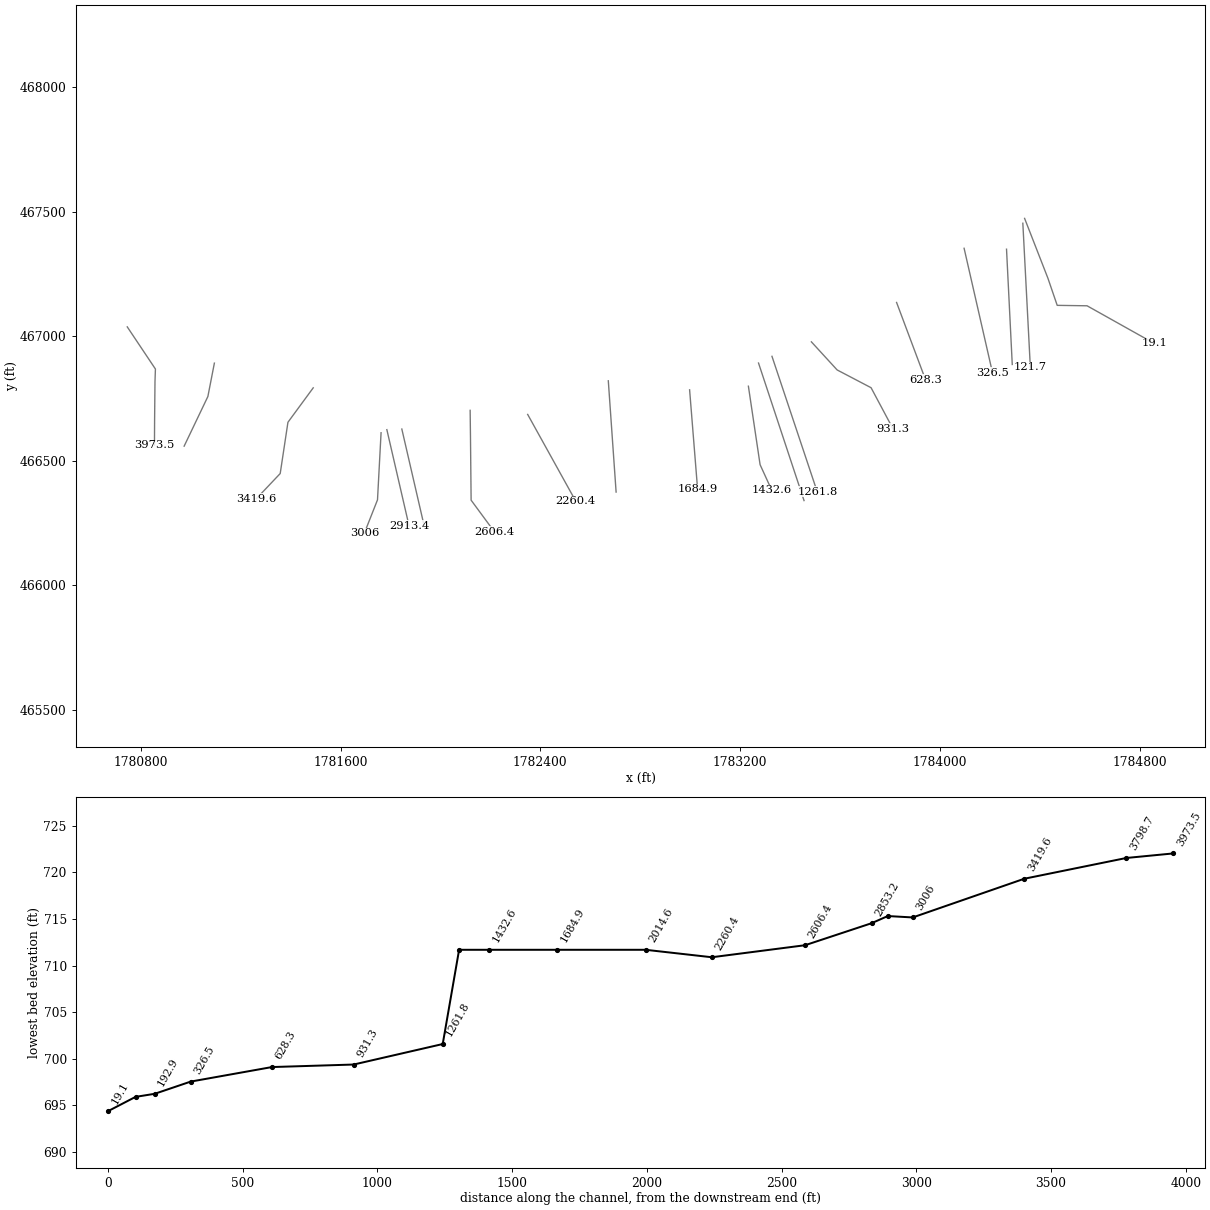
HEC-RAS study DAVISCK.prj: DAVISCK

--- DAVISCK.g01 (geometry) --- (continued)

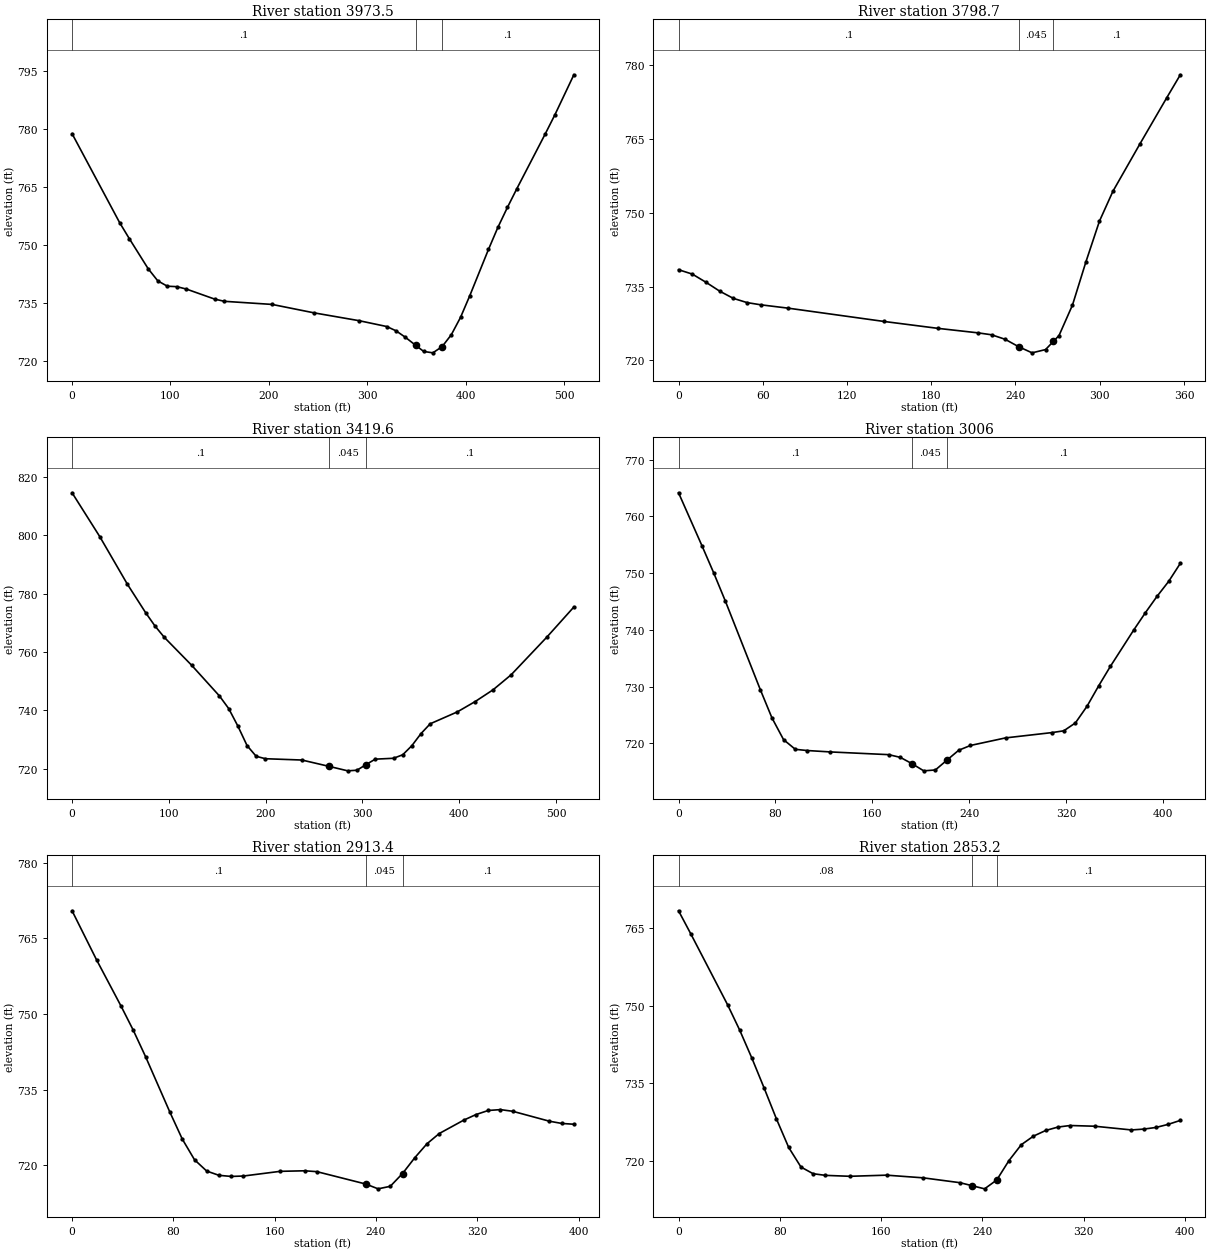
Type RM Length L Ch R = 1 ,3973.5  ,187.9,174.8,161.8
XS GIS Cut Line= 5
     1780745.509       467038.07     1780858.308      466868.919
     1780856.572      466817.857      1780854.98      466658.747
      1780854.45       466562.22
#Sta/Elev= 30
       0  778.71    48.4  755.68    58.1   751.6    77.4  743.77    87.1  740.66
    96.8  739.27   106.5  739.15   116.2  738.53   145.2  735.91   154.9  735.36
   203.3  734.56   245.9  732.38   291.8  730.35   319.9  728.84   329.3  727.73
   338.6  726.09   349.1  724.01   357.4   722.4   366.7  722.04   376.1  723.65
   385.4   726.7   394.8   731.2   404.2   736.8   423.2  748.77   432.8  754.49
   442.5  759.66   452.1  764.51   481.1  778.74   490.8  783.63     510  793.94
#Mann= 3 , 0 , 0
       0      .1       0   349.1    .045       0   376.1      .1       0
Bank Sta=349.1,376.1
XS Rating Curve= 0 ,0
Exp/Cntr=0.3,0.1

Type RM Length L Ch R = 1 ,3798.7  ,369.6,379.1,387.5
XS GIS Cut Line= 3
     1781094.462      466892.621      1781068.42      466758.506
     1780973.368      466559.288
#Sta/Elev= 25
       0  738.41     9.8  737.52    19.5  735.87    29.3  734.06      39   732.6
    48.8  731.74    58.6  731.29    78.1  730.61   146.2  727.92   184.6  726.52
   213.4   725.6     223  725.21   232.6   724.3   242.2   722.8   251.8  721.55
   261.4  722.21     267  723.87     271  725.06   280.6  731.25   290.2  740.04
   299.8  748.26   309.4  754.32   328.6  763.91   347.8  773.32   357.4  777.94
#Mann= 3 , 0 , 0
       0      .1       0   242.2    .045       0     267      .1       0
Bank Sta=242.2,267
XS Rating Curve= 0 ,0
Exp/Cntr=0.3,0.1

Type RM Length L Ch R = 1 ,3419.6  ,410.1,413.7,417
XS GIS Cut Line= 4
     1781490.344      466793.333     1781389.098      466655.163
     1781358.115      466449.359     1781262.536      466348.392
#Sta/Elev= 30
       0  814.52    28.6  799.52    57.1  783.24    76.1  773.42    85.6  768.94
    95.2  765.06   123.7  755.41   152.3  744.94   161.8  740.65   171.3  734.64
   180.8  727.96   190.2   724.3   199.7  723.47   237.5  723.02   265.9  720.82
   284.8  719.32   294.3  719.53   303.7  721.45   313.2  723.32   332.1  723.62
   341.6  724.82     351  727.92   360.5  732.08     370  735.43     398   739.5
   416.5  743.05     435  747.08   453.6   752.2   490.6  765.14   518.4  775.41
#Mann= 3 , 0 , 0
       0      .1       0   265.9    .045       0   303.7      .1       0
Bank Sta=265.9,303.7
XS Rating Curve= 0 ,0
Exp/Cntr=0.3,0.1

Type RM Length L Ch R = 1 ,3006    ,84.2,92.5,100.8
XS GIS Cut Line= 3
     1781762.113      466613.146     1781747.811      466343.663
     1781694.879      466209.399
#Sta/Elev= 30
       0  764.14    19.3  754.83    28.9   750.1    38.6  745.09    67.5  729.47
    77.1   724.5    86.7  720.66    96.4  718.96     106  718.75   125.3   718.5
   173.5  718.02   183.1  717.54   192.8  716.42   202.4  715.17     212  715.32
   221.9  717.12   231.3   718.8     241  719.64   269.9  720.97   308.4  721.91
     318  722.22   327.6  723.61   337.2  726.55   346.8  730.14   356.5  733.58
   375.7  739.96   385.3     743   394.9  745.88   404.6  748.54   414.2  751.71
#Mann= 3 , 0 , 0
       0      .1       0   192.8    .045       0   221.9      .1       0
Bank Sta=192.8,221.9
XS Rating Curve= 0 ,0
Exp/Cntr=0.3,0.1

Type RM Length L Ch R = 1 ,2913.4  ,60.6,60.3,59.8
XS GIS Cut Line= 2
     1781785.295      466625.534     1781874.222      466239.309
#Sta/Elev= 30
       0  770.46    19.3  760.75    38.7  751.55    48.3  746.79      58  741.56
    77.3   730.5      87  725.21    96.7  721.09   106.3  718.85     116     718
   125.7  717.78   135.3  717.86   164.3  718.79   183.7   718.9   193.3  718.73
     232  716.27   241.7  715.32   251.3  715.82     261  718.36   270.7   721.5
   280.3  724.26     290  726.29   309.3  728.94     319  730.05   328.7  730.86
   338.3  731.03     348   730.7     377  728.73   386.7  728.29   396.3  728.13
#Mann= 3 , 0 , 0
       0      .1       0     232    .045       0     261      .1       0
Bank Sta=232,261
XS Rating Curve= 0 ,0
Exp/Cntr=0.3,0.1

Type RM Length L Ch R = 1 ,2853.2  ,253.1,246.7,240.2
XS GIS Cut Line= 2
     1781845.258      466627.971     1781934.185      466241.747
#Sta/Elev= 30
       0  768.42     9.7  763.94    38.7  750.23    48.3   745.3      58  739.83
    67.7  734.02    77.3  728.11      87  722.57    96.7  718.77   106.3  717.48
     116  717.16   135.3  716.98   164.3   717.2   193.3  716.68   222.3  715.74
     232  715.15   241.7  714.55   251.3  716.26     261  720.04   270.7   723.1
   280.3  724.76     290  725.86   299.7  726.52   309.3  726.82   328.7  726.68
   357.7  725.96   367.3  726.12     377  726.44   386.7  727.04   396.3  727.81
#Mann= 3 , 0 , 0
       0     .08       0     232    .045       0   251.3      .1       0
Bank Sta=232,251.3
XS Rating Curve= 0 ,0
Exp/Cntr=0.3,0.1

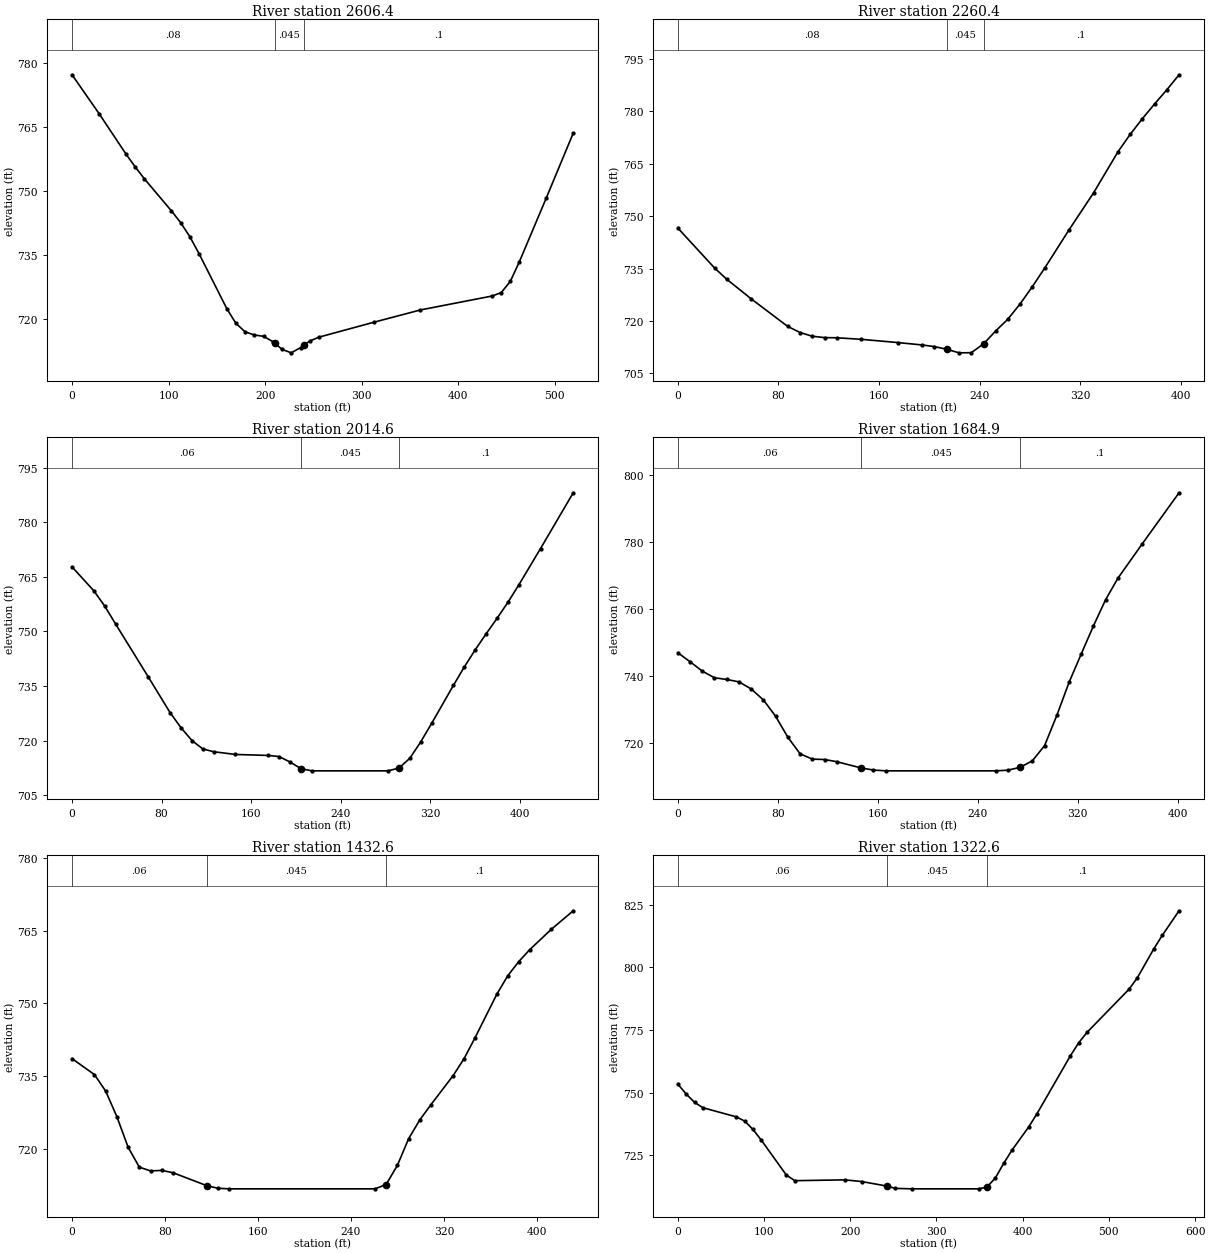
Type RM Length L Ch R = 1 ,2606.4  ,330.7,346,361.2
XS GIS Cut Line= 4
     1782118.888      466703.088      1782120.19      466600.223
     1782122.794      466342.411     1782216.544      466214.807
#Sta/Elev= 30
       0  777.17    28.1  768.06    56.1  758.56    65.5  755.62    74.8  752.89
   102.9  745.37   112.4  742.64     122  739.33   131.5  735.37   160.2  722.54
   169.7  719.08   179.3  717.08   188.8  716.37   198.4  716.04   207.9  714.82
   209.8  714.46   217.5     713     227  712.19   236.6  713.41   239.8  713.93
   246.1  714.95   255.7  715.86     313  719.37   360.7  722.21   435.2  725.48
   444.5  726.28   453.8  728.88   463.2  733.46   491.1  748.39     519  763.54
#Mann= 3 , 0 , 0
       0     .08       0   209.8    .045       0   239.8      .1       0
Bank Sta=209.8,239.8
XS Rating Curve= 0 ,0
Exp/Cntr=0.3,0.1

Type RM Length L Ch R = 1 ,2260.4  ,259.1,245.8,232.6
XS GIS Cut Line= 2
     1782349.314      466686.639     1782542.108      466338.027
#Sta/Elev= 30
       0   746.6    29.2  735.18    38.9  731.95    58.3  726.35    87.4  718.44
    97.2  716.71   106.9  715.65   116.6  715.26   126.3  715.21   145.8  714.77
   174.9  713.84   194.3  713.15     204  712.68   213.8  711.92   223.5   710.9
   233.2  710.94     243  713.46   252.6  717.15   262.3  720.53   272.1  724.92
   281.8  729.85   291.5   735.1   310.9  746.07   330.4  756.66   349.8  768.41
   359.5   773.4   369.2   777.9   378.9  782.11   388.7  786.19   398.4  790.48
#Mann= 3 , 0 , 0
       0     .08       0   213.8    .045       0     243      .1       0
Bank Sta=213.8,243
XS Rating Curve= 0 ,0
Exp/Cntr=0.3,0.1

Type RM Length L Ch R = 1 ,2014.6  ,329.3,329.7,330
XS GIS Cut Line= 2
     1782672.273      466821.578     1782703.523      466374.963
#Sta/Elev= 30
       0  767.73    19.5  761.15    29.2  756.97    38.9  752.04    68.1   737.5
    87.6  727.68    97.3  723.56   107.1  720.03   116.8  717.72   126.5  716.95
     146   716.2   175.2  715.93   184.9  715.63   194.7  714.13   204.4  712.32
   214.1   711.7   282.2   711.7     292  712.45   301.7  715.14   311.4  719.62
   321.2  724.73   340.6  735.15   350.4  740.24   360.1  744.94   369.8   749.3
   379.6  753.58   389.3  757.98     399  762.74   418.5  772.78   447.7  788.09
#Mann= 3 , 0 , 0
       0     .06       0   204.4    .045       0     292      .1       0
Bank Sta=204.4,292
XS Rating Curve= 0 ,0
Exp/Cntr=0.3,0.1

Type RM Length L Ch R = 1 ,1684.9  ,250.2,252.3,254.3
XS GIS Cut Line= 2
     1782997.921      466785.425      1783029.95      466385.742
#Sta/Elev= 30
       0  746.95     9.8  744.26    19.6  741.45    29.3  739.48    39.1  738.97
    48.9  738.26    58.7  736.14    68.5  732.84    78.2     728      88  721.73
    97.8  716.79   107.6   715.2   117.4  715.08   127.1  714.43   146.7  712.56
   156.5  711.93   166.2   711.7   254.3   711.7     264  711.89   273.8  712.75
   283.6  714.68   293.4  719.22   303.2  728.23     313  738.12   322.7  746.56
   332.5  754.96   342.3  762.83   352.1  769.21   371.6  779.48     401   794.7
#Mann= 3 , 0 , 0
       0     .06       0   146.7    .045       0   273.8      .1       0
Bank Sta=146.7,273.8
XS Rating Curve= 0 ,0
Exp/Cntr=0.3,0.1

Type RM Length L Ch R = 1 ,1432.6  ,105,110.1,115.3
XS GIS Cut Line= 3
     1783233.368      466799.889     1783280.251      466484.898
     1783326.992      466382.248
#Sta/Elev= 27
       0  738.59    19.3  735.29      29  731.86    38.6  726.59    48.2  720.32
    57.9  716.17    67.6   715.4    77.2  715.51    86.8  715.03   115.8  712.37
   125.4  711.82   135.1   711.7   260.6   711.7   270.2  712.59   279.9  716.54
   289.5  722.02   299.2  725.94   308.8  729.09   327.9  735.09   337.3  738.59
   346.7  742.89   365.5  751.91   374.9  755.71   384.3  758.62   393.6  761.05
   412.4  765.31   431.2  769.12
#Mann= 3 , 0 , 0
       0     .06       0   115.8    .045       0   270.2      .1       0
Bank Sta=115.8,270.2
XS Rating Curve= 0 ,0
Exp/Cntr=0.3,0.1

Type RM Length L Ch R = 1 ,1322.6  ,60.7,60.8,60.8
XS GIS Cut Line= 2
     1783273.949      466892.893     1783456.241       466340.81
#Sta/Elev= 30
       0  753.47     9.7  749.51    19.4  746.18    29.1  744.06    67.8  740.41
    77.5  738.72    87.2  735.38    96.9  731.08     126  717.13   135.7  714.96
   193.8  715.28   213.2  714.61   242.2  712.82   251.9  711.89   271.3   711.7
   348.8   711.7   358.5  712.42   368.2  715.97   377.9  721.81   387.6  727.13
     407  736.39   416.7  741.73   455.4   764.8   465.1     770   474.8  774.18
   523.3   791.3     533  795.88   552.3  807.53     562  812.84   581.4  822.62
#Mann= 3 , 0 , 0
       0     .06       0   242.2    .045       0   358.5      .1       0
Bank Sta=242.2,358.5
XS Rating Curve= 0 ,0
Exp/Cntr=0.3,0.1

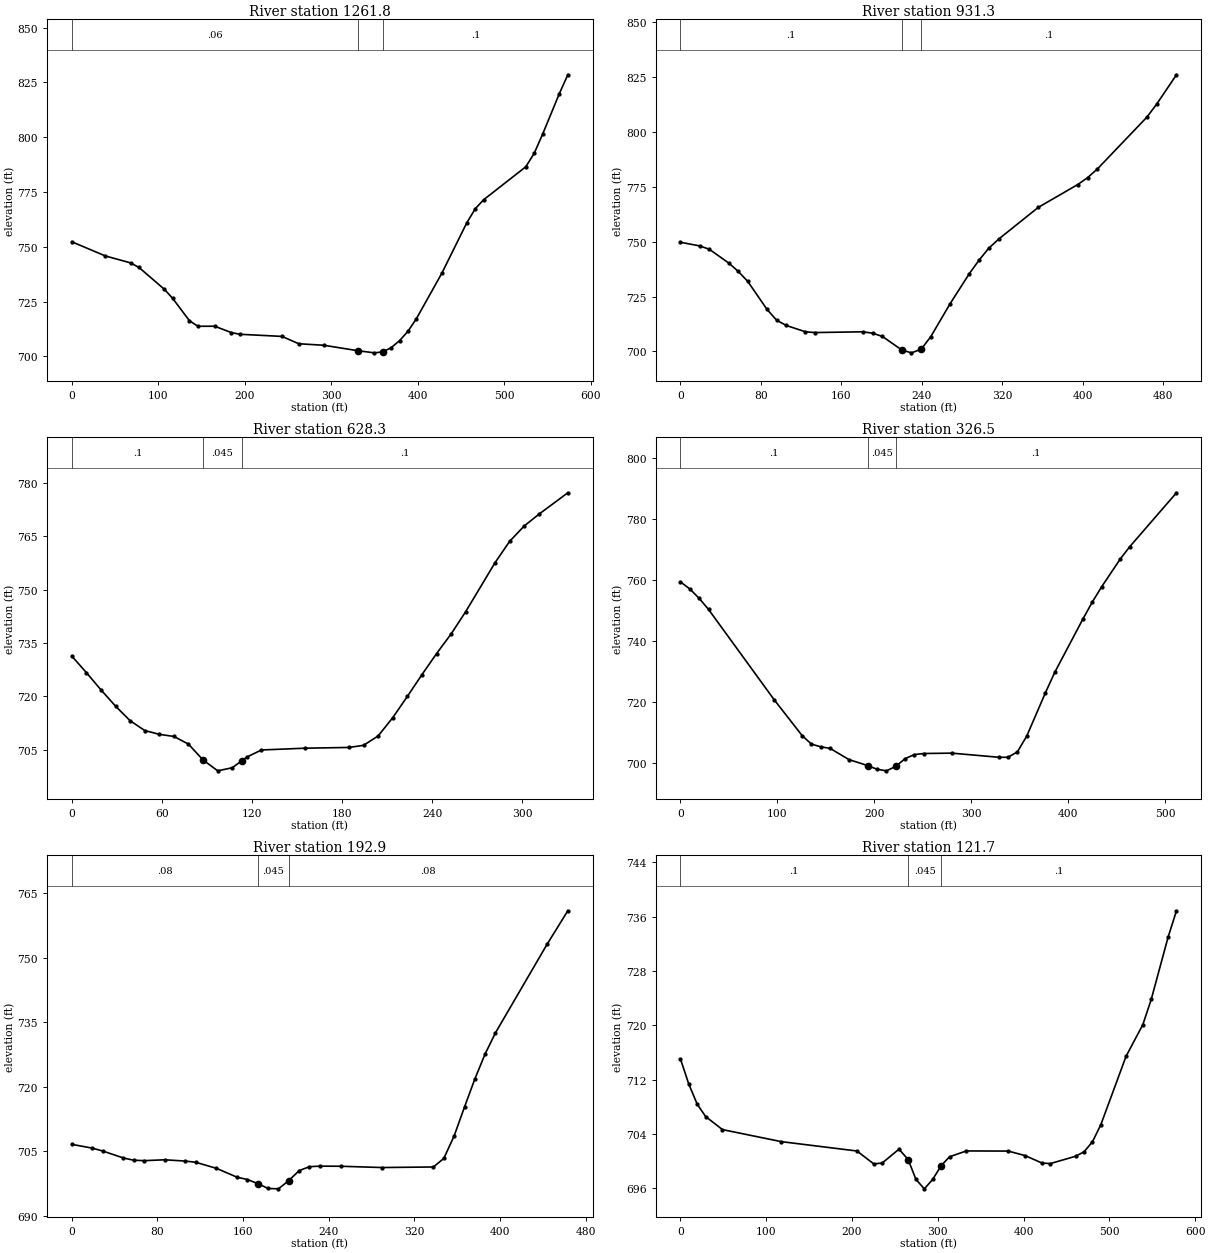
Type RM Length L Ch R = 1 ,1261.8  ,307.4,330.5,353.7
XS GIS Cut Line= 2
     1783327.833      466919.867     1783509.121      466375.927
#Sta/Elev= 30
       0  752.28    38.9   745.8      68  742.64    77.7  740.55   106.9  730.64
   116.6  726.45     136  716.26   145.8  713.71   165.2  713.74   184.6  710.82
   194.4  710.06     243  709.09   262.4  705.74   291.5  705.04   330.4  702.58
   349.8  701.59   359.6  702.02   369.3  703.98     379  707.18   388.7  711.48
   398.4   717.2   427.6   737.8   456.7     761   466.5  767.39   476.2  771.49
   524.8  786.49   534.5  792.61   544.2  801.31   563.6  819.89   573.4  828.49
#Mann= 3 , 0 , 0
       0     .06       0   330.4    .045       0   359.6      .1       0
Bank Sta=330.4,359.6
XS Rating Curve= 0 ,0
Exp/Cntr=0.3,0.1

Type RM Length L Ch R = 1 ,931.3   ,324.9,303,280.9
XS GIS Cut Line= 4
     1783485.698       466977.97     1783588.837      466865.192
      1783724.75      466793.862     1783812.467      466629.031
#Sta/Elev= 30
       0   749.7    19.1  748.04    28.7  746.51    47.8  740.31    57.3  736.51
    66.9  731.89      86  719.18    95.5  714.28   105.1  711.86   124.2  708.97
   133.7  708.62   181.6  708.96   191.2   708.3   200.8  706.83     220  700.68
   229.6  699.39   239.2     701   248.8  706.74     268  721.74   287.1  735.41
   296.7  741.51   306.3  746.92   316.2   751.1   355.5  765.52   394.8  775.93
   404.6  779.06   414.4  783.05   463.6  806.62   473.4  812.59     493  825.89
#Mann= 3 , 0 , 0
       0      .1       0     220    .045       0   239.2      .1       0
Bank Sta=220,239.2
XS Rating Curve= 0 ,0
Exp/Cntr=0.3,0.1

Type RM Length L Ch R = 1 ,628.3   ,305.8,301.8,297.8
XS GIS Cut Line= 2
     1783826.926      467136.053     1783942.596      466826.635
#Sta/Elev= 30
       0  731.36     9.7  726.72    19.4  721.88    29.2  717.26    38.9  713.18
    48.6  710.44    58.3  709.37      68  708.78    77.7  706.62    87.4  702.18
    97.2  699.12   106.9     700   113.3  701.98   116.6     703   126.3  704.98
   155.4  705.48   184.6  705.69   194.3  706.29     204  708.92   213.7  714.04
   223.5  720.05   233.2  726.16   242.9  732.05   252.6  737.57   262.3  743.83
   281.8  757.55   291.5  763.54   301.2  767.86   310.9  771.14   330.3  777.21
#Mann= 3 , 0 , 0
       0      .1       0    87.4    .045       0   113.3      .1       0
Bank Sta=87.4,113.3
XS Rating Curve= 0 ,0
Exp/Cntr=0.3,0.1

Type RM Length L Ch R = 1 ,326.5   ,138.9,133.6,128.4
XS GIS Cut Line= 2
     1784097.349      467353.556      1784211.04       466854.47
#Sta/Elev= 30
       0  759.48     9.7  757.17    19.3   754.1      29  750.46    96.6  720.91
   125.6   709.1   135.2  706.32   144.9  705.42   154.5  704.92   173.8  701.26
   193.2  699.28   202.8  698.09   212.5  697.56   222.1  698.99   231.8  701.55
   241.4  702.89   251.1  703.24   280.1  703.36   328.4  702.01     338     702
   347.7  703.77   357.3  708.91   376.7  723.18   386.3  729.86   415.3   747.3
     425  752.86   434.6  757.84   453.9     767   463.6     771   511.9  788.69
#Mann= 3 , 0 , 0
       0      .1       0   193.2    .045       0   222.1      .1       0
Bank Sta=193.2,222.1
XS Rating Curve= 0 ,0
Exp/Cntr=0.3,0.1

Type RM Length L Ch R = 1 ,192.9   ,71.1,71.1,71.2
XS GIS Cut Line= 2
     1784267.273      467349.894     1784290.233      466887.156
#Sta/Elev= 30
       0  706.59    19.3   705.7      29  705.03    48.3  703.41    57.9   702.9
    67.6   702.8    86.9     703   106.2   702.7   115.8  702.42   135.1  701.01
   154.4  698.95   164.1  698.42   173.7  697.46   183.4  696.34     193  696.25
   202.7  698.17   212.4  700.49     222   701.4   231.6  701.52     251   701.5
   289.6   701.2   337.8  701.33   347.5  703.33   357.1  708.53   366.8  715.26
   376.4  721.74   386.1  727.62   395.7  732.49     444  753.11   463.3  760.86
#Mann= 3 , 0 , 0
       0     .08       0   173.7    .045       0   202.7     .08       0
Bank Sta=173.7,202.7
XS Rating Curve= 0 ,0
Exp/Cntr=0.3,0.1

Type RM Length L Ch R = 1 ,121.7   ,94.3,102.6,111
XS GIS Cut Line= 2
     1784332.621      467454.099     1784362.646      466876.559
#Sta/Elev= 30
       0  715.04     9.8  711.32    19.6  708.37    29.4  706.56      49  704.64
   117.6  702.87   205.8  701.49   225.4  699.59   235.2  699.72   254.8  701.76
   265.5  700.23   274.5  697.32   284.3  695.92   294.1  697.31   303.9  699.32
   313.7  700.64   333.3   701.5   382.3  701.48   401.9  700.81   421.5  699.72
   431.3  699.64   460.7  700.72   470.5  701.37   480.3  702.84   490.1  705.36
   519.5  715.43   539.1   720.1   548.9  723.82   568.5  732.97   578.3  736.86
#Mann= 3 , 0 , 0
       0      .1       0   265.5    .045       0   303.9      .1       0
Bank Sta=265.5,303.9
XS Rating Curve= 0 ,0
Exp/Cntr=0.3,0.1

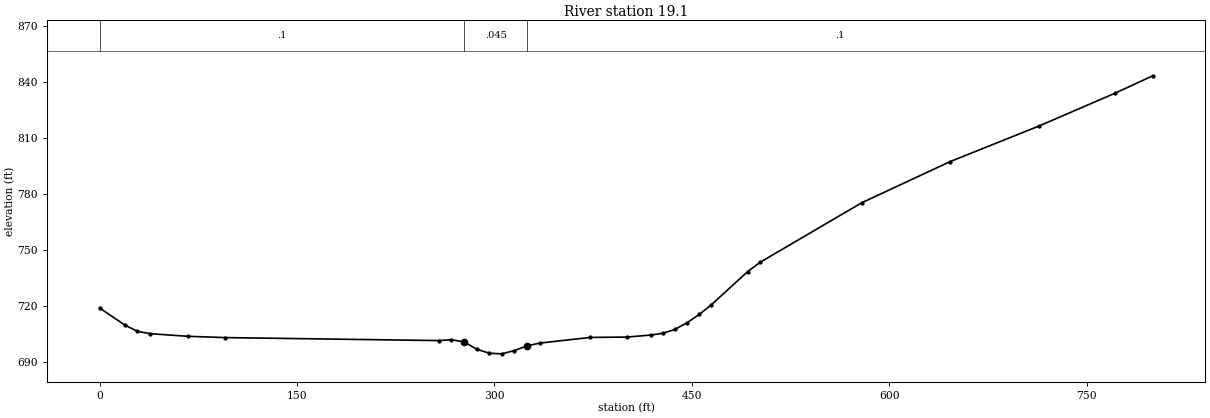
Type RM Length L Ch R = 1 ,19.1    ,18.5,19.1,19.7
XS GIS Cut Line= 5
     1784339.686      467473.527     1784433.077      467233.317
     1784470.261      467124.461     1784589.882      467122.723
     1784858.268      466971.995
#Sta/Elev= 30
       0  718.94    19.1  709.81    28.6  706.47    38.2  705.19    66.8  703.78
    95.4  703.08   257.7  701.48   267.3  701.94   276.9  700.75   286.5  696.88
   296.1   694.7   305.7  694.38   315.2  696.15   324.8  698.66   334.4  700.14
   372.8  703.17   400.4  703.36   418.8  704.44     428  705.39   437.2  707.49
   446.4  711.07   455.6  715.48   464.8  720.64   492.4  738.43     502  743.47
     579  775.26   646.3  797.35   713.6  816.34   771.4  833.91   800.2  843.29
#Mann= 3 , 0 , 0
       0      .1       0   276.9    .045       0   324.8      .1       0
Bank Sta=276.9,324.8
XS Rating Curve= 0 ,0
Exp/Cntr=0.3,0.1

Chan Stop Cuts=-1
Use User Specified Reach Order=0
Composite Channel Slope=5